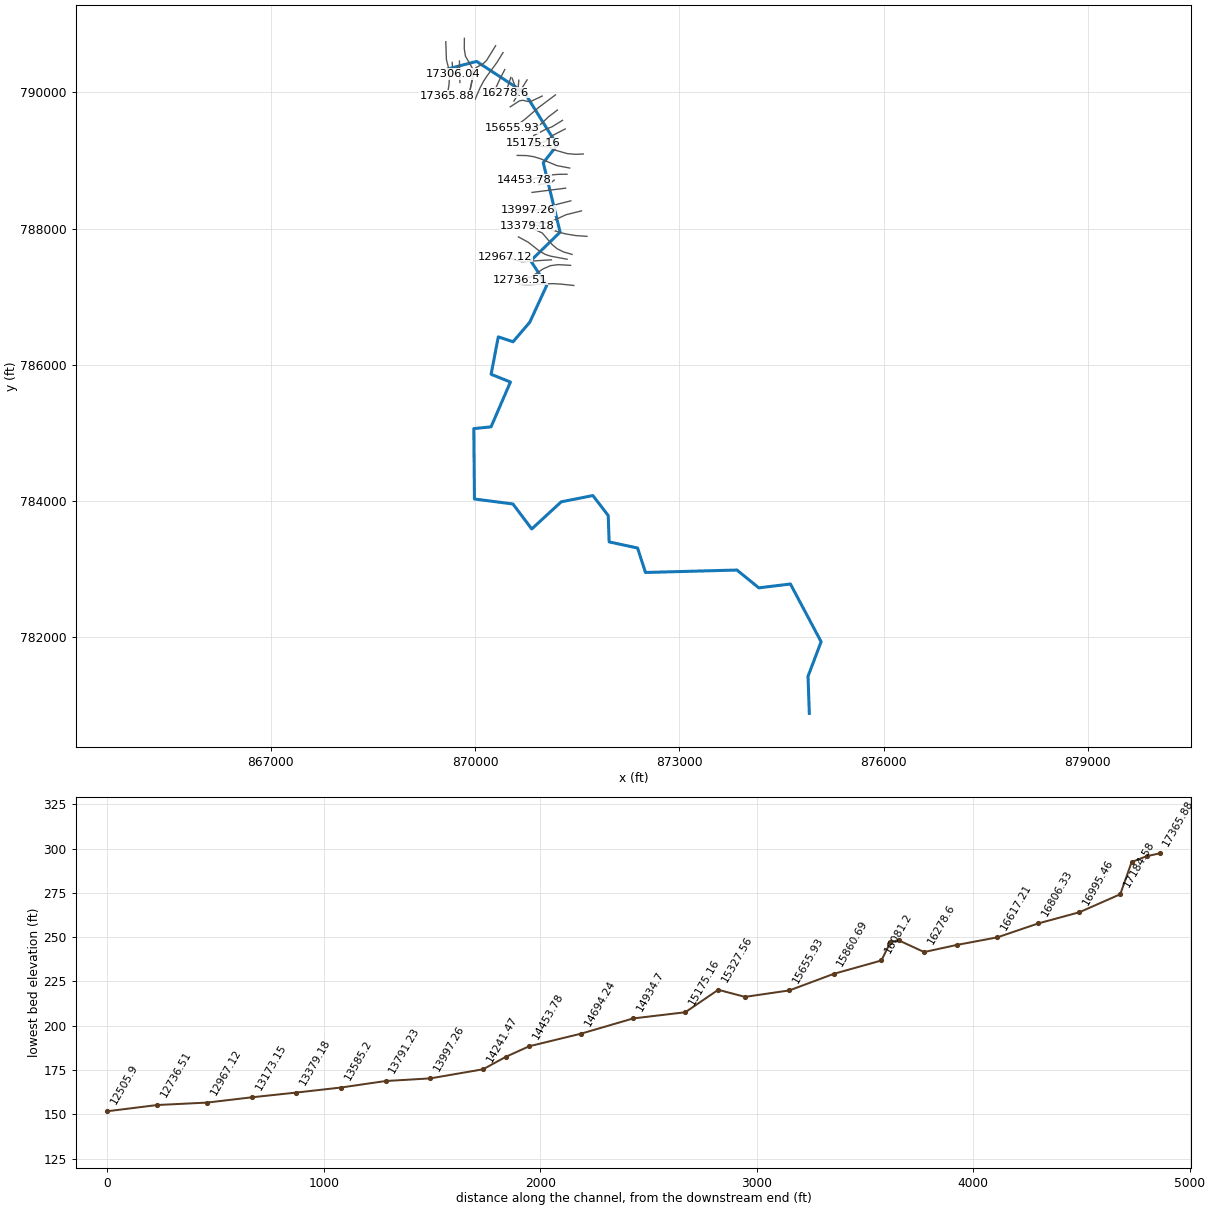
--- 11677_ras.prj (project) ---

Proj Title=11677
Current Plan=p01
Default Exp/Contr=0.3,0.1
English Units
Geom File=g01
Flow File=f01
Plan File=p01
Y Axis Title=Elevation
X Axis Title(PF)=Main Channel Distance
X Axis Title(XS)=Station
BEGIN DESCRIPTION:
RFD model 11677 exported to HEC-RAS
END DESCRIPTION:

--- 11677_ras.p01 (plan) ---

Plan Title=Plan 01
Program Version=4.10
Short Identifier=Plan 01
Geom File=g01
Flow File=f01
Subcritical Flow
Calc Critical at every XS
Secant Critical Depth

--- 11677_ras.f01 (steady flow) ---

Flow Title=Flow 01
Program Version=5.01
Number of Profiles= 6
Profile Names=10yr,25yr,50yr,100yr,100plus,500yr
River Rch & RM=11677,55,17365.88
  546.87  805.37 1030.95 1212.18 1769.78  2386.1
River Rch & RM=11677,55,17236.92
  550.05  810.13  1037.1 1219.47 1780.42 2398.66
River Rch & RM=11677,55,16995.46
  555.91   818.9 1048.47 1232.95 1800.11 2421.91
River Rch & RM=11677,55,16617.21
  559.95  824.96 1056.31 1242.26  1813.7 2437.96
River Rch & RM=11677,55,16428.08
  563.97  830.99 1064.13 1251.55 1827.26 2453.96
River Rch & RM=11677,55, 16278.6
   703.2 1038.69 1332.49 1569.21 2291.05    2988
River Rch & RM=11677,55,16160.19
  750.92 1110.51 1425.83 1680.25 2453.17 3173.19
River Rch & RM=11677,55, 16081.2
  755.81  1117.9 1435.47 1691.76 2469.97 3192.43
River Rch & RM=11677,55,15860.69
  757.82 1120.95 1439.46 1696.53 2476.93 3200.44
River Rch & RM=11677,55,15655.93
  766.35 1133.86 1456.29 1716.62 2506.26 3233.97
River Rch & RM=11677,55,15451.16
  774.08 1145.55 1471.53 1734.79 2532.79  3264.2
River Rch & RM=11677,55,15327.56
  776.08 1148.59  1475.5 1739.54 2539.72 3272.13
River Rch & RM=11677,55,15175.16
  778.09 1151.63 1479.47 1744.28 2546.66 3280.06
River Rch & RM=11677,55, 14934.7
  926.06 1376.55 1773.67 2096.25 3060.53 3861.18
River Rch & RM=11677,55,14694.24
  937.06 1393.31 1795.64 2122.57 3098.96 3904.19
River Rch & RM=11677,55,14453.78
  960.16 1428.34 1841.38 2177.22 3178.74  3992.6
River Rch & RM=11677,55,14345.78
  961.99 1431.15 1845.08 2181.68 3185.25 3999.94
River Rch & RM=11677,55,14241.47
  967.12 1439.02 1855.45 2194.16 3203.47 4020.44
River Rch & RM=11677,55,13997.26
  974.81 1450.83    1871 2212.86 3230.77 4051.12
River Rch & RM=11677,55,13791.23
  992.27 1477.67 1906.35 2255.42 3292.91  4120.9
River Rch & RM=11677,55, 13585.2
  996.99 1484.92  1915.9 2266.91  3309.7 4139.72
River Rch & RM=11677,55,13379.18
 1000.98 1491.05 1923.98 2276.63 3323.89 4155.62
River Rch & RM=11677,55,13173.15
 1011.16 1506.67 1944.55 2301.38 3360.02 4195.98
River Rch & RM=11677,55,12967.12
 1035.95  1544.5 1994.16 2360.86 3446.86 4291.95
River Rch & RM=11677,55, 12505.9
 1041.84 1553.65  2006.3 2375.55 3468.31 4316.17
River Rch & RM=11677,55,12275.28
 1046.98 1561.65 2016.92 2388.44 3487.13 4337.49
River Rch & RM=11677,55,12044.67
 1052.14 1569.68 2027.58 2401.35 3505.97 4358.77
River Rch & RM=11677,55,11855.62
 1174.71 1755.59 2270.51 2691.64  3929.8 4817.23
River Rch & RM=11677,55,11528.82
 1185.78 1772.81 2293.37 2719.34 3970.24 4862.12
River Rch & RM=11677,55,11249.78
 1192.51 1783.26 2307.23 2736.12 3994.74 4889.25
River Rch & RM=11677,55,11043.52
 1195.65 1788.08 2313.59 2743.78 4005.92 4901.44
River Rch & RM=11677,55,   10904
 1222.48  1829.3 2367.89 2809.14 4101.34 5005.23
River Rch & RM=11677,55,10779.52
 1251.65 1873.65 2425.94 2878.59 4202.75 5113.51
River Rch & RM=11677,55,10331.73
  1265.1 1894.47 2453.51 2911.91 4251.39 5166.65
River Rch & RM=11677,55,9883.948
 1382.84 2074.26 2689.49 3194.97 4664.66 5606.23
River Rch & RM=11677,55,9436.164
 1400.79  2102.4 2727.05 3240.68 4731.39 5679.23
River Rch & RM=11677,55, 8988.38
 1444.77 2170.44  2817.1 3349.48 4890.25 5849.42
River Rch & RM=11677,55,8540.596
 1455.32 2186.86 2838.92 3375.94 4928.87 5891.03
River Rch & RM=11677,55,7747.818
 1488.31 2238.28 2907.29 3458.91    5050 6021.43
River Rch & RM=11677,55,7091.981
 1503.77 2262.68 2939.98 3498.82 5108.27 6084.97
River Rch & RM=11677,55,6549.269
 1515.12 2280.65 2964.11 3528.35 5151.39 6132.14
River Rch & RM=11677,55,6423.464
 1531.03 2305.79 2997.82 3569.55 5211.55  6197.7
River Rch & RM=11677,55,6053.253
 1544.15 2326.55 3025.68 3603.63  5261.3 6251.92
River Rch & RM=11677,55,5549.681
 1545.63 2328.89 3028.83 3607.49 5266.93 6258.07
Boundary for River Rch & Prof#=11677,55,1
Up Type= 0
Dn Type= 2
Boundary for River Rch & Prof#=11677,55,2
Up Type= 0
Dn Type= 2
Boundary for River Rch & Prof#=11677,55,2
Up Type= 0
Dn Type= 2
Boundary for River Rch & Prof#=11677,55,2
Up Type= 0
Dn Type= 2
Boundary for River Rch & Prof#=11677,55,2
Up Type= 0
Dn Type= 2
Boundary for River Rch & Prof#=11677,55,2
Up Type= 0
Dn Type= 2

--- 11677_ras.g01 (geometry) ---

Geom Title=11677
Program Version=4.10

River Reach=11677,55
Reach XY= 30
869611.097788841790347.451408654870023.597788811 790455.09029752
870730.561439097789992.804895476871207.231027484789226.188548416
871002.904875308788966.465793833871249.818902969787948.153686196
870818.337334901787527.687928572871053.562590539787165.670570403
870804.145624012786624.758971676870558.609546512786338.105243832
870342.347788811786410.645853058870236.792233288 785861.34029752
 870520.82001105785747.451408625870236.097788811785089.118075266
869982.705662221785063.578901425869992.325998694784029.684434086
870556.851433367783956.631842017870833.468774974783589.550145984
871266.653344363783988.423630819871731.356177211784079.818912312
871956.236677736783787.729186371871970.125566572783399.534741923
872387.486677736783309.951408595872503.265034258782950.771721095
873846.581006497782986.579012737 874167.76156202782725.077276647
874632.171284258782781.500887766875082.648462147781933.532105237
874890.457800508781425.861739025874909.465349585780881.810989067

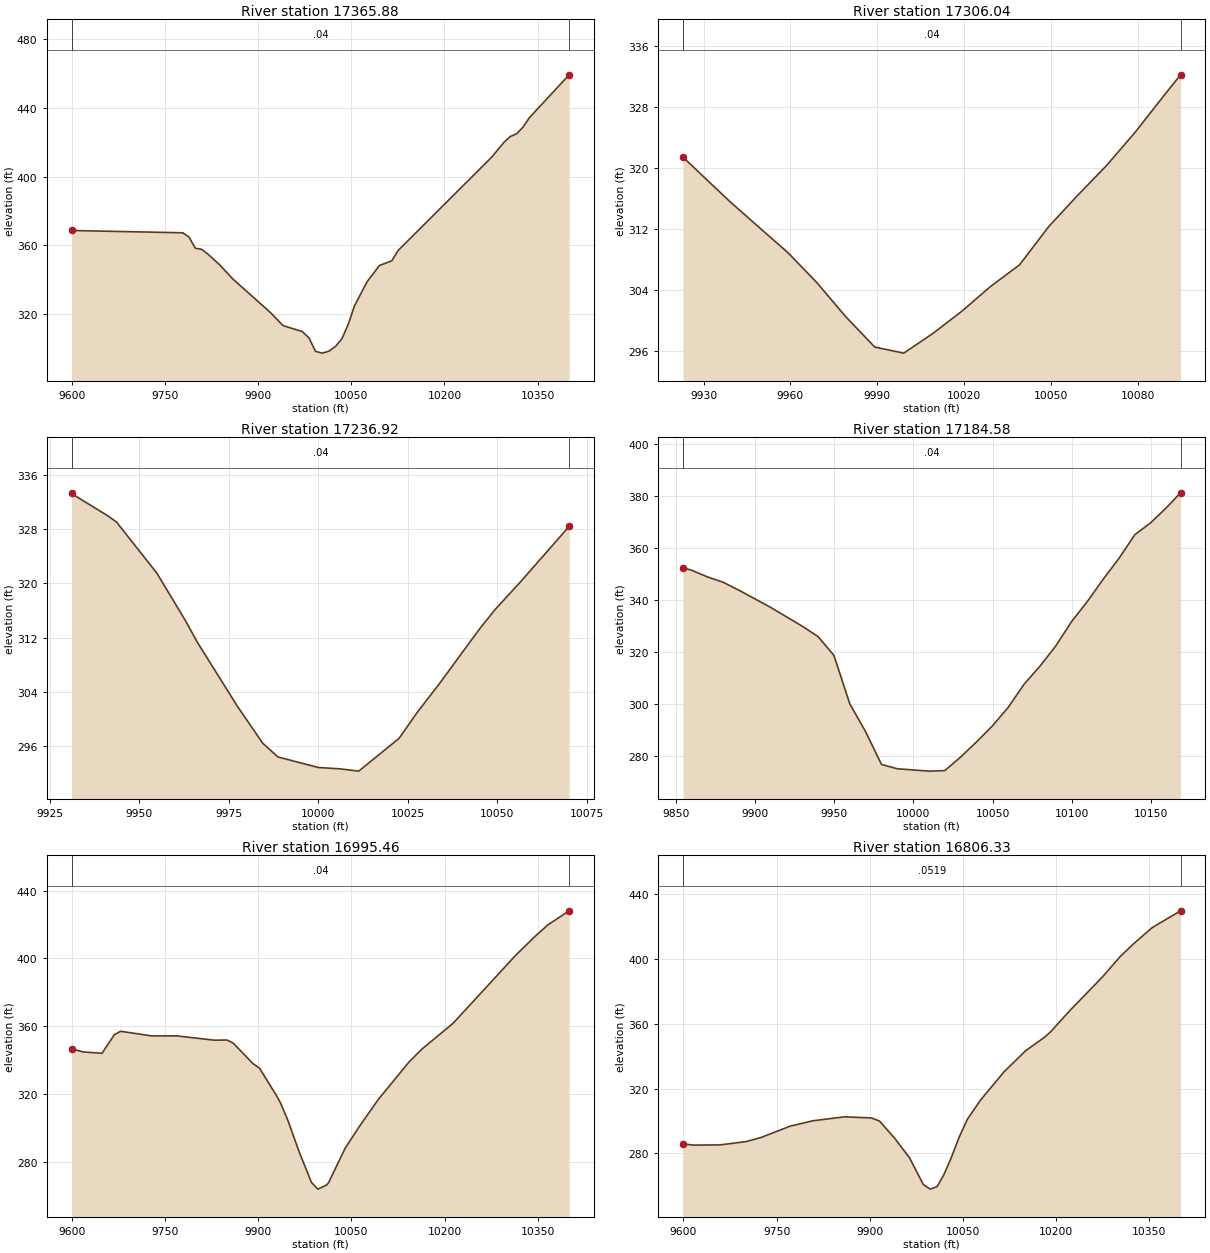
Type RM Length L Ch R = 1 ,17365.88,59.838700,59.838700,59.838700
XS GIS Cut Line= 6
869571.281012641790744.275025046869580.771433523790480.114514952
869623.192175778790315.311515936869628.404514652790270.201519656
869618.146219457790109.820644595869592.151154934789951.805847023
#Sta/Elev= 30
9599.046368.62489778.403367.27949788.419364.75379798.435358.33739808.464357.6926
9818.508354.94669838.596 348.3719858.683340.47869919.348320.95619939.803313.3006
9970.903309.80769981.512306.19139992.293 298.28210003.12297.263910013.94298.4192
10024.37301.144410034.79305.632610044.94314.057610055.08324.838610075.13338.7212
10095.15 348.25510115.16350.988110125.16356.941610275.88411.222710296.07420.0021
10306.16423.341810316.26424.902810326.42428.6942 10336.6434.174610400.91 459.204
#Mann= 3 , 0 , 0
9599.046    0.04       09599.046    0.04       010400.91    0.04       0
#XS Ineff= 2 , 0
       0                               0
Bank Sta=9599.046,10400.91
Exp/Cntr=0.3,0.1

Type RM Length L Ch R = 1 ,17306.04,69.119400,69.119400,69.119400
XS GIS Cut Line= 2
869665.927819639790441.276171312869672.872264057790269.401171312
#Sta/Elev= 19
9922.819321.4363  9929.1319.16819939.108315.57239949.116312.21379959.124308.8807
9969.133304.94279979.141300.45299989.149296.47929999.157295.685710009.17298.2538
10019.17301.167810029.18304.449310039.19307.2826 10049.2312.276110059.21316.3851
10069.21320.305910079.22324.729910089.23329.575110094.83332.2359
#Mann= 3 , 0 , 0
9922.819    0.04       09922.819    0.04       010094.83    0.04       0
#XS Ineff= 2 , 0
       0                               0
Bank Sta=9922.819,10094.83
Exp/Cntr=0.3,0.1

Type RM Length L Ch R = 1 ,17236.92,52.339100,52.339100,52.339100
XS GIS Cut Line= 2
869759.677819639790396.137282431869695.441708475790272.873393551
#Sta/Elev= 21
9931.117333.33979932.399332.81349941.239329.96169943.676329.03839954.952321.5128
9962.877314.57349966.228311.36449977.505301.86749984.516296.48279988.781294.4494
10000.06 292.90410006.15 292.70110011.33292.368310022.61 297.20110027.79301.0963
10033.89305.257910045.16 313.35510049.43316.157510056.44320.188110067.72326.9604
10070.11328.4297
#Mann= 3 , 0 , 0
9931.117    0.04       09931.117    0.04       010070.11    0.04       0
#XS Ineff= 2 , 0
       0                               0
Bank Sta=9931.117,10070.11
Exp/Cntr=0.3,0.1

Type RM Length L Ch R = 1 ,17184.58,189.125400,189.125400,189.125400
XS GIS Cut Line= 2
869771.830597401790460.373393551869778.775041819790146.137282431
#Sta/Elev= 30
9854.397352.42939859.772351.50879869.774 348.9659879.776346.87519889.779343.7997
9909.784337.20889929.789329.96199939.791325.96279949.793318.70539959.796 300.107
9969.798289.38429979.801276.79739989.803275.133510009.81  274.2210019.81274.4199
10029.81279.623410039.82285.458110049.82291.588410059.82298.709710069.82307.6115
10079.83314.525910089.83322.311710099.83331.698610109.83339.455410119.84348.0173
10129.84356.075810139.84365.154910149.84369.745410159.84375.583810168.71 381.271
#Mann= 3 , 0 , 0
9854.397    0.04       09854.397    0.04       010168.71    0.04       0
#XS Ineff= 2 , 0
       0                               0
Bank Sta=9854.397,10168.71
Exp/Cntr=0.3,0.1

Type RM Length L Ch R = 1 ,16995.46,189.125200,189.125200,189.125200
XS GIS Cut Line= 6
869844.326530441790794.041935031869843.017953032790638.872203064
869860.358984541790531.567525602869970.636041982790340.446826444
869959.761039178790198.000279581869925.585064482790031.522085844
#Sta/Elev= 30
9599.181346.67129618.239 344.8979648.264344.1195 9668.28355.13319678.288357.0846
9728.317354.36469768.415354.38989829.109  351.859849.556351.93399859.779350.0834
9891.403338.02659901.986335.37149929.574319.02089935.636314.97729947.771304.4968
9965.514286.3715 9985.63267.97879995.977264.035110010.25266.472810013.39267.9558
 10039.8 288.04210062.38300.718110093.18 316.81110143.24339.161110163.37346.5141
10213.69361.750910315.13402.067410345.92413.069410366.45419.788910400.81428.1014
#Mann= 3 , 0 , 0
9599.181    0.04       09599.181    0.04       010400.81    0.04       0
#XS Ineff= 2 , 0
       0                               0
Bank Sta=9599.181,10400.81
Exp/Cntr=0.3,0.1

Type RM Length L Ch R = 1 ,16806.33,189.125300,189.125300,189.125300
XS GIS Cut Line= 6
 870303.04168443790685.457371898870168.953466181790468.457445931
870115.667701646790418.300843867 870022.05928438790368.022521019
869995.941483317790340.527717792869925.568699809790020.614234114
#Sta/Elev= 30
9599.112285.72229616.379284.99199659.323285.13769700.973287.18289724.907289.6947
9771.998 296.728 9808.35300.01989859.557302.48899902.861301.80319915.898 299.841
9940.664289.05359964.203277.15239986.366 260.6249997.448 257.76810008.61259.3077
 10019.3266.498310031.14276.921810043.65289.431310057.23300.899510078.67312.8819
10116.46330.344710151.27343.369310181.73 351.70610191.89 355.23410222.35368.1676
10273.12388.230410303.89401.716510324.43409.279610355.23419.5408 10400.8429.8997
#Mann= 3 , 0 , 0
9599.112  0.0519       09599.112  0.0519       0 10400.8  0.0519       0
#XS Ineff= 2 , 0
       0                               0
Bank Sta=9599.112,10400.8
Exp/Cntr=0.3,0.1

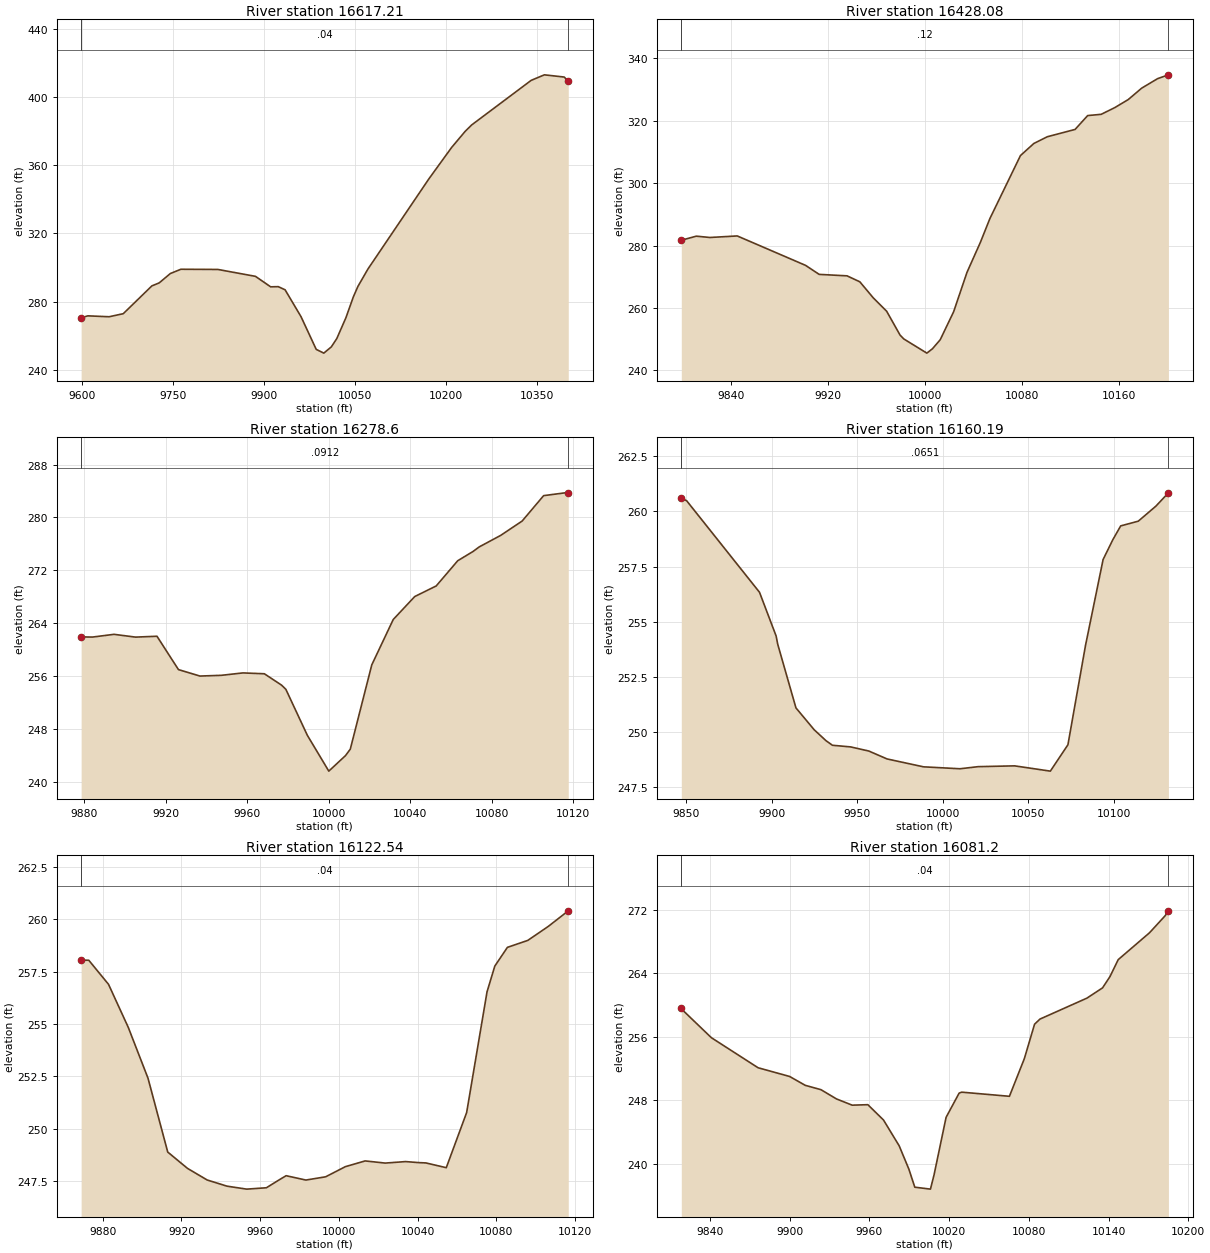
Type RM Length L Ch R = 1 ,16617.21,189.125200,189.125200,189.125200
XS GIS Cut Line= 6
870412.069296964790584.482446474870318.865796677790434.691933772
870174.170538048790237.701516971870126.723982372790165.749088129
 870070.90012498790059.358143911870001.889206057789898.900746462
#Sta/Elev= 30
9599.015270.58879610.068271.72319645.036271.19099668.349272.98589715.486289.2771
9727.465291.01029745.831296.49889763.174298.9996 9824.07298.89429886.004 294.853
9911.008288.7158 9923.51 288.8179934.777286.97249961.015271.22449986.019252.0849
9998.521249.890510010.89253.550110019.91258.436410035.12270.8156 10047.1282.8162
10054.73288.991310071.06 299.08910171.28351.838910208.89  370.3210231.03379.6918
10241.92383.516610339.89 409.63410361.66412.869810394.32411.562710400.96409.1182
#Mann= 3 , 0 , 0
9599.015    0.04       09599.015    0.04       010400.96    0.04       0
#XS Ineff= 2 , 0
       0                               0
Bank Sta=9599.015,10400.96
Exp/Cntr=0.3,0.1

Type RM Length L Ch R = 1 ,16428.08,149.483700,149.483700,149.483700
XS GIS Cut Line= 6
870437.804968648790335.985359429870375.892121471790216.440597327
870348.027904977790157.423553056 870347.22140895790155.593371601
870302.850585935790060.304767187 870261.06866927789975.222671782
#Sta/Elev= 30
 9799.11281.74089811.481 283.0459822.743282.62579845.266 283.1189901.573 273.693
9912.835270.79849935.825270.33019946.387268.41139957.446263.27499968.504258.9751
9979.563251.3333 9982.67250.091310001.65245.556410006.26246.949710012.69249.8585
10023.72258.803810034.75271.447210045.78281.045310053.64288.686210078.87308.8929
 10089.9312.759210101.02314.918410123.92317.2648 10134.3321.702910145.44322.1009
10156.59324.238110167.73326.824410178.87330.499610191.98333.5389 10200.9334.7629
#Mann= 3 , 0 , 0
 9799.11    0.12       0 9799.11    0.12       0 10200.9    0.12       0
#XS Ineff= 2 , 0
       0                               0
Bank Sta=9799.11,10200.9
Exp/Cntr=0.3,0.1

Type RM Length L Ch R = 1 , 16278.6,118.402300,118.402300,118.402300
XS GIS Cut Line= 2
870526.387889051790220.301778969870450.107507103789993.522265058
#Sta/Elev= 28
9878.423261.90849884.017261.88539894.567262.29899905.118261.87719915.668262.0079
9926.219256.95639936.769255.9783 9947.32256.08899957.871256.45349968.421256.3241
9976.876254.59919978.972253.96969989.522247.004410000.07241.574710008.24 243.917
10010.62244.901710021.17257.668910031.72264.544710042.27268.021610052.83269.6306
10063.38273.444810070.98274.865610073.93 275.54110084.48277.285110095.03  279.46
10105.58283.308110116.13283.736410117.69283.6706
#Mann= 3 , 0 , 0
9878.423  0.0912       09878.423  0.0912       010117.69  0.0912       0
#XS Ineff= 2 , 0
       0                               0
Bank Sta=9878.423,10117.69
Exp/Cntr=0.3,0.1

Type RM Length L Ch R = 1 ,16160.19,37.657400,37.657400,37.657400
XS GIS Cut Line= 3
870545.973392516790207.931987301870616.068878621790016.200216472
870597.514191121789937.858202562
#Sta/Elev= 25
9847.198260.6033 9850.32260.48369892.909256.33529902.611254.35479903.557253.9784
9914.204251.09619924.851250.10719931.734249.61329935.499249.40439946.146249.3298
9956.793249.14259967.441248.78419988.735248.427110010.03248.339410020.68 248.435
10041.97 248.47110062.85248.232410073.13249.4272 10083.4253.929110093.68257.8201
10099.37258.718210103.96259.343410114.23259.557410124.51260.236710131.85260.8419
#Mann= 3 , 0 , 0
9847.198  0.0651       09847.198  0.0651       010131.85  0.0651       0
#XS Ineff= 2 , 0
       09927.043        10051.38       0
Bank Sta=9847.198,10131.85
Exp/Cntr=0.3,0.1

Type RM Length L Ch R = 1 ,16122.54,41.336000,41.336000,41.336000
XS GIS Cut Line= 3
870643.454713196 790178.86981371870630.954713196790030.258702591
870605.260268718 789935.11981371
#Sta/Elev= 30
9868.976 258.0549872.859258.04719882.895256.8992 9892.93 254.8469902.965252.4198
9913.001 248.8949923.036248.11519933.071247.55969943.107247.26649953.142247.1242
9963.177247.18919969.848247.57749973.213247.76469983.248247.55749993.283247.7119
10003.32248.196410013.35248.469710018.11248.422910023.56248.366910033.92248.4381
10040.95248.387710044.28248.374110054.63248.147110064.99250.780110075.35256.5393
 10079.3257.767510085.71258.662410096.07258.994610106.43 259.65810116.66260.4061
#Mann= 3 , 0 , 0
9868.976    0.04       09868.976    0.04       010116.66    0.04       0
#XS Ineff= 2 , 0
       09934.257        10035.18       0
Bank Sta=9868.976,10116.66
Exp/Cntr=0.3,0.1

Type RM Length L Ch R = 1 , 16081.2,220.506800,220.506800,220.506800
XS GIS Cut Line= 2
870765.537194639790184.223219931870571.743791848789872.916796327
#Sta/Elev= 30
9818.364259.6905 9819.38259.37499841.008255.89879876.147 252.1139899.904251.0129
9911.684249.89449923.463 249.3519935.242248.17689947.022247.39679958.801247.4557
 9970.58245.5258 9982.36242.27969989.679239.33479994.139237.058810005.92236.8151
 10008.6238.5912 10017.7245.866810027.52 248.91710029.48249.034210065.37248.5134
10076.59253.255210084.29257.598310088.37258.245810123.71260.884110135.49262.1814
10141.06263.602210147.27265.738710170.83269.123210182.61271.272210185.06271.8878
#Mann= 3 , 0 , 0
9818.364    0.04       09818.364    0.04       010185.06    0.04       0
#XS Ineff= 2 , 0
       0                               0
Bank Sta=9818.364,10185.06
Exp/Cntr=0.3,0.1

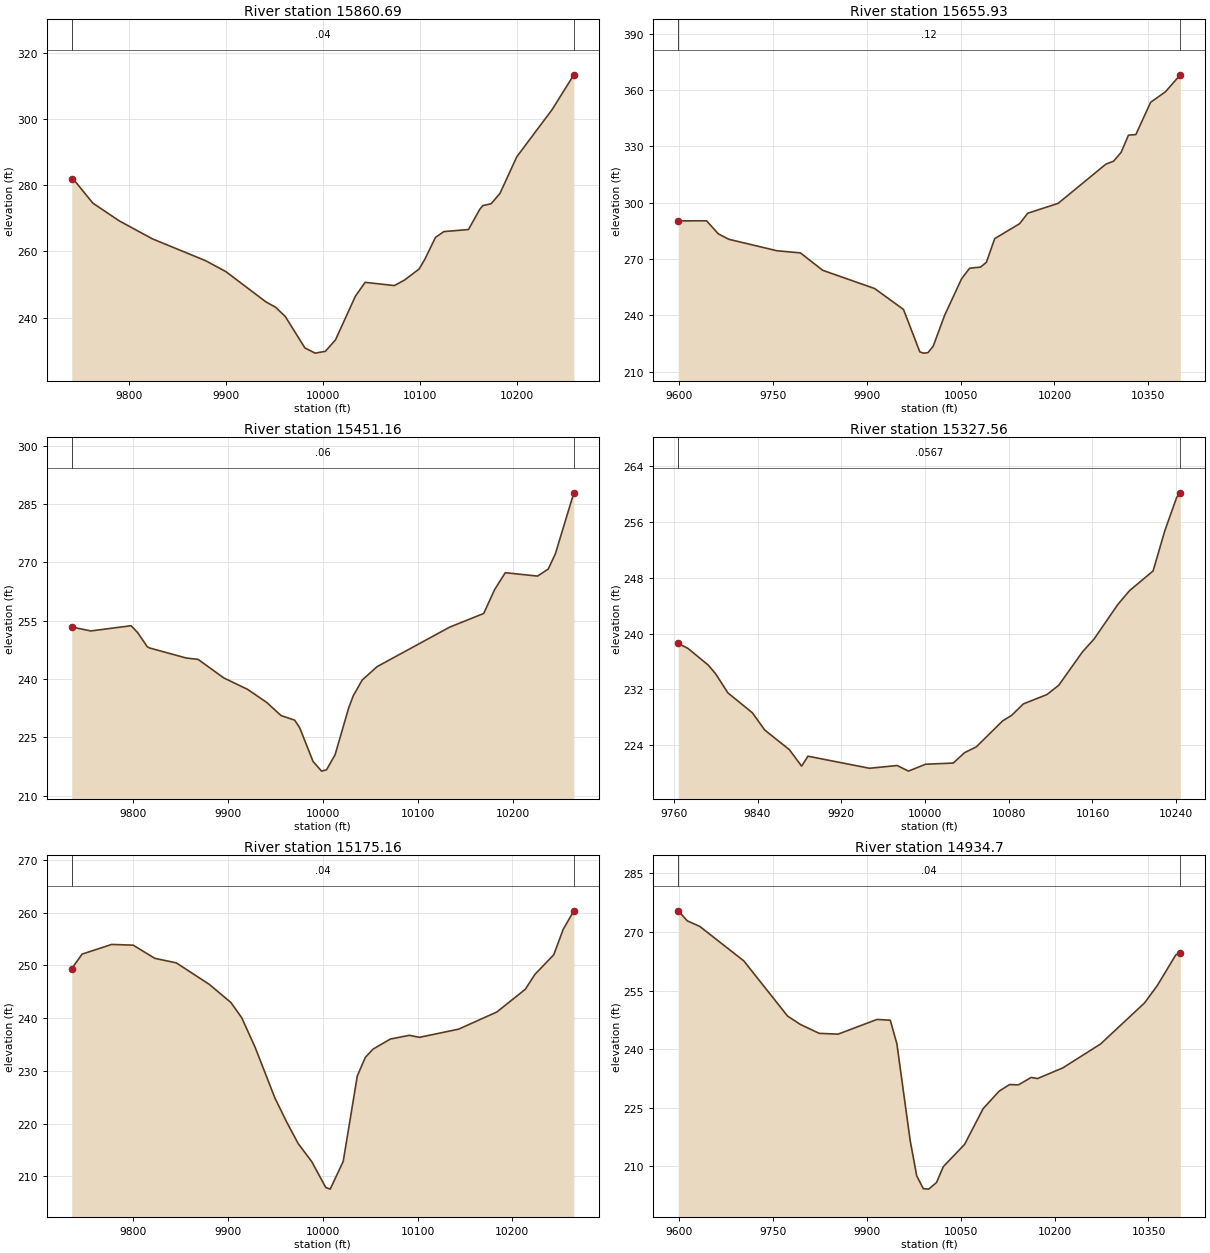
Type RM Length L Ch R = 1 ,15860.69,204.768900,204.768900,204.768900
XS GIS Cut Line= 6
870986.604823965789946.585355596870823.109821637789869.297239099
870777.635735551789866.643315542870703.577255354789884.769999291
870654.062527951789876.506174376870517.578842557789788.125133094
#Sta/Elev= 30
9741.033281.98589744.017281.34629762.837274.57189790.144269.20499824.205 263.793
9879.075257.19749900.168253.85879941.162 244.7759951.203243.13639961.205240.3683
9981.488 230.8429992.014229.2594 10002.6229.795910013.09 233.27910033.54 246.432
10043.64250.6525 10073.8249.676110084.16251.319210099.32254.676410105.33257.6736
10116.19 264.23410124.86265.983110150.24 266.61210161.82272.679210164.96273.8243
10173.69274.420110182.72  277.5210200.03288.577910236.51302.851310258.93 313.359
#Mann= 3 , 0 , 0
9741.033    0.04       09741.033    0.04       010258.93    0.04       0
#XS Ineff= 2 , 0
       0                               0
Bank Sta=9741.033,10258.93
Exp/Cntr=0.3,0.1

Type RM Length L Ch R = 1 ,15655.93,204.768800,204.768800,204.768800
XS GIS Cut Line= 6
871181.236606712789963.393657442870936.702258835789780.252819729
870757.685616455789625.928832029870707.102682108789585.226400642
 870629.65355368789530.125823085 870544.83488311789476.996942026
#Sta/Elev= 30
9599.018290.3718 9644.29290.41289663.065283.45949679.747280.57969756.733274.4522
9794.214273.31479829.883264.02739912.728254.33479958.847  243.189984.896220.5863
9990.763219.91839997.921220.170610006.23 223.58710024.49240.050610051.59259.5306
10064.49265.150210081.83265.744310091.16268.283610104.49280.921510144.35288.8901
10157.19294.434810205.83299.703610282.04320.591910294.32322.172810306.37326.8453
10318.17336.044310329.97336.361510353.57353.569110377.17359.125610400.96368.1822
#Mann= 3 , 0 , 0
9599.018    0.12       09599.018    0.12       010400.96    0.12       0
#XS Ineff= 2 , 0
       0                               0
Bank Sta=9599.018,10400.96
Exp/Cntr=0.3,0.1

Type RM Length L Ch R = 1 ,15451.16,123.595600,123.595600,123.595600
XS GIS Cut Line= 6
871211.142530991789741.653601827871080.445160207789642.301063594
870978.205767566789544.878933838 870935.82938591789509.809321782
870874.100813863789469.553777506 870791.19017831789425.960221427
#Sta/Elev= 30
9736.038253.37239755.987252.35789798.423 253.7049805.419251.89999815.444248.2823
9817.777  247.989856.085245.40959868.867245.03799895.918240.2592 9921.01237.3078
9941.113233.9343 9956.08230.57759970.381229.39229975.591227.48449989.723218.7591
9998.687216.277310003.89216.626810012.86220.4786 10027.1232.484110031.98 235.672
10041.35239.712810057.01243.165110133.33253.338110169.15 256.859 10180.5262.9556
 10191.8267.342310225.69266.476710236.99268.279210244.47272.211510263.89287.9061
#Mann= 3 , 0 , 0
9736.038    0.06       09736.038    0.06       010263.89    0.06       0
#XS Ineff= 2 , 0
       0                               0
Bank Sta=9736.038,10263.89
Exp/Cntr=0.3,0.1

Type RM Length L Ch R = 1 ,15327.56,152.404400,152.404400,152.404400
XS GIS Cut Line= 4
 871285.40231213789589.947378591871129.778313726789494.231733546
 871043.70309341789461.178848937870861.912227988789366.840407431
#Sta/Elev= 30
9764.211238.58319773.655237.84699792.743235.49199799.904234.23469811.644231.4914
9835.124228.62779846.864226.16359870.344 223.3569882.084220.99159888.184222.4129
9946.914 220.6839973.457221.07719984.169220.272710000.56 221.26110027.02221.4291
10037.73222.914210048.92223.743510074.24227.485310082.72228.260210093.99229.9141
10116.52231.250710127.79232.583110150.32237.341310161.59239.224210184.12 244.141
10195.38246.138710217.92248.966510229.18254.756110240.45 259.50610243.93260.1659
#Mann= 3 , 0 , 0
9764.211  0.0567       09764.211  0.0567       010243.93  0.0567       0
#XS Ineff= 2 , 0
       09972.692                       0
Bank Sta=9764.211,10243.93
Exp/Cntr=0.3,0.1

Type RM Length L Ch R = 1 ,15175.16,240.459500,240.459500,240.459500
XS GIS Cut Line= 6
871324.817479942789463.498501724871142.374853181789369.320388464
871067.812010675789301.640332495871028.601750114789277.425230277
870964.284401928789260.146890966870853.790998792789253.154039082
#Sta/Elev= 30
  9734.9249.38979745.828252.12879777.015253.96129799.781253.82599822.548251.3272
9845.315250.46679880.118246.39639902.983 242.9519914.416240.05789928.564234.4483
9949.387224.87099961.732220.34419974.078216.19999988.321212.801410003.14207.8933
 10007.8207.585610021.54212.8361 10036.4229.023610044.83232.530910052.93234.1098
10071.31236.0277 10091.4 236.73810102.03236.354410143.41237.904710183.78241.1569
10213.82245.456410223.83248.257210243.86251.997210253.87256.826510265.09260.3312
#Mann= 3 , 0 , 0
  9734.9    0.04       0  9734.9    0.04       010265.09    0.04       0
#XS Ineff= 2 , 0
       0                               0
Bank Sta=9734.9,10265.09
Exp/Cntr=0.3,0.1

Type RM Length L Ch R = 1 , 14934.7,240.459500,240.459500,240.459500
XS GIS Cut Line= 6
871589.492576302789095.729835333871477.853863482789091.089220203
871357.515411826 789100.65330303871185.715005852789150.172612431
871079.108774554 789198.25316252870807.914437079 789224.32966722
#Sta/Elev= 30
9599.076 275.418  9613.6272.84449633.643271.40599703.695262.60429773.763248.4402
9793.879246.33079824.107244.02889854.256 243.8159916.646247.59459937.743247.3779
9948.292241.3045 9969.39216.63019979.939207.50489990.487204.2224    9999204.1087
10011.48205.796810022.43209.879410056.38215.572910085.92224.716710111.38229.1912
10128.08230.898210142.38230.820110162.66232.728310172.79232.442510213.15235.1645
10273.55241.303110343.74 251.82710363.76 256.18910393.77264.156810400.85264.5379
#Mann= 3 , 0 , 0
9599.076    0.04       09599.076    0.04       010400.85    0.04       0
#XS Ineff= 2 , 0
       0                               0
Bank Sta=9599.076,10400.85
Exp/Cntr=0.3,0.1

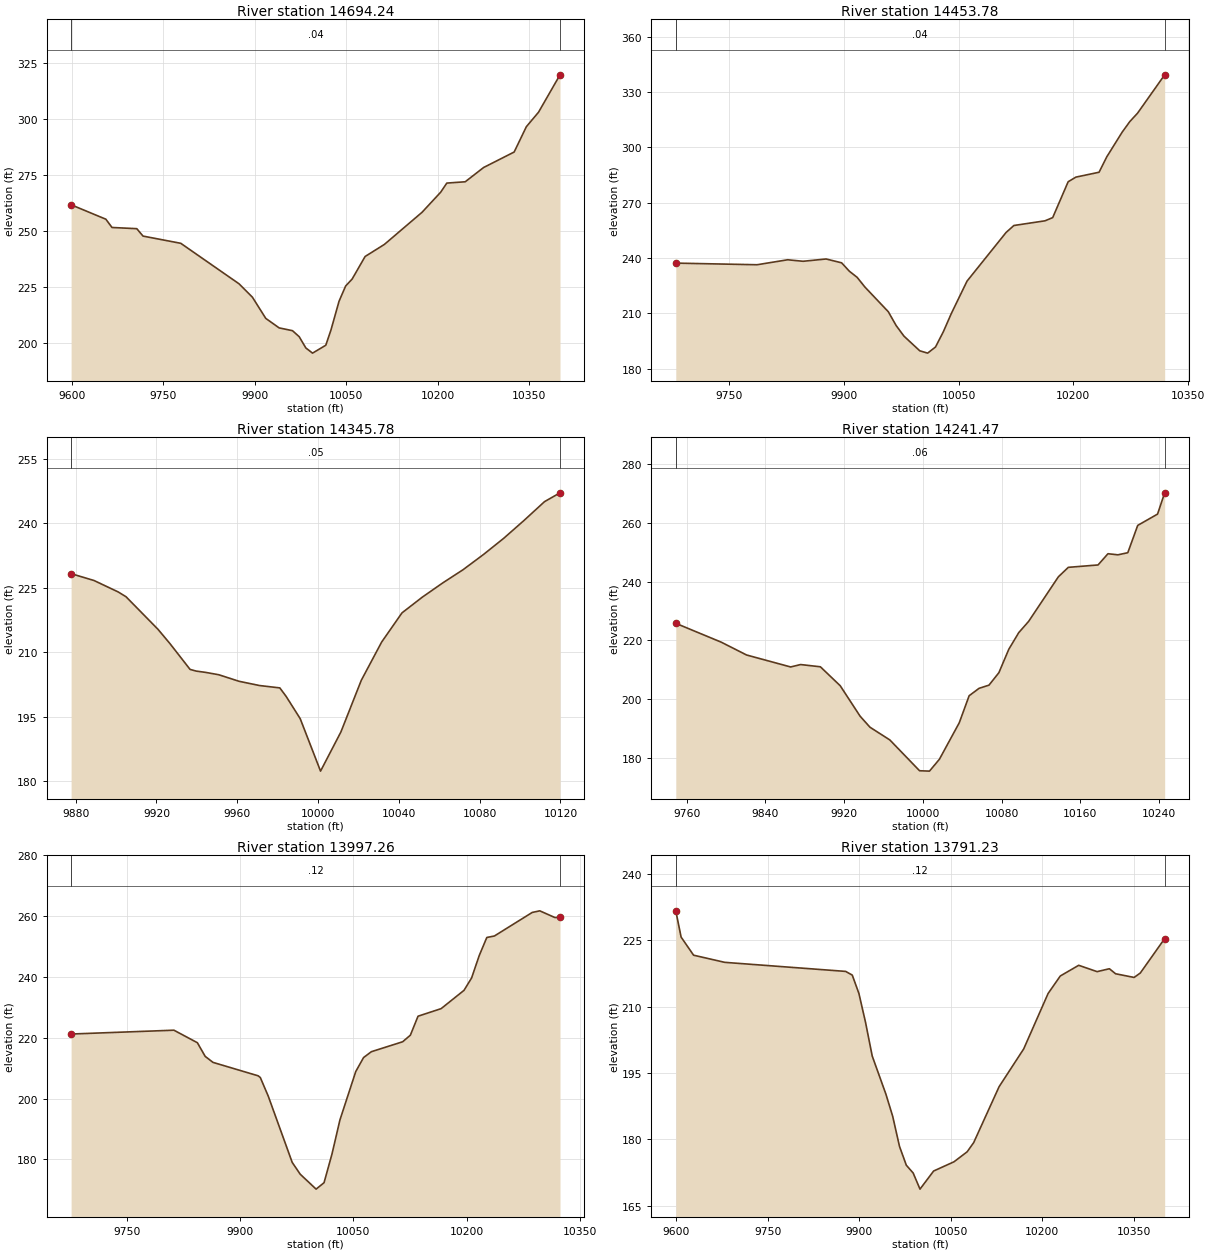
Type RM Length L Ch R = 1 ,14694.24,240.459400,240.459400,240.459400
XS GIS Cut Line= 6
871391.591988888788889.352737752871203.323334362788925.122939726
870961.291821065789025.929848281870868.801522881789055.035172508
870755.011709024789072.811860849870619.800785057789075.129019368
#Sta/Elev= 30
9599.062261.71019656.027255.26849666.162251.57619706.777251.04029717.006 247.738
9778.941244.5109 9874.54226.43739896.451220.46099918.361211.00639940.271206.7795
9962.182205.52999973.137202.85429984.092197.81099995.047195.519410016.76199.0315
10025.29205.869210038.48218.642410049.33225.463510060.03228.585710081.24238.6254
10112.83244.006610174.66258.353510205.19267.309310215.27271.379410245.49271.9717
10275.66278.338110325.73285.242910345.73296.540410365.73303.017410400.93319.6807
#Mann= 3 , 0 , 0
9599.062    0.04       09599.062    0.04       010400.93    0.04       0
#XS Ineff= 2 , 0
       0                               0
Bank Sta=9599.062,10400.93
Exp/Cntr=0.3,0.1

Type RM Length L Ch R = 1 ,14453.78,107.998300,107.998300,107.998300
XS GIS Cut Line= 6
871351.128787661788798.314925431871236.323674703 788797.60900405
871148.751804326 788791.18910179871087.925363357788781.023656906
870896.765649683788738.652632364870719.709202717788717.516121387
#Sta/Elev= 30
9680.753237.17049786.884236.28679826.926238.9837 9846.96238.16299877.113239.4084
9897.335237.33219907.474232.76789917.613229.46599927.751224.20529958.334210.8081
9968.601203.29169978.868197.53619999.403189.625410009.69188.370210019.97191.6968
10030.26200.020210040.55209.791210061.12227.406110112.12253.780910122.32257.5667
10162.88260.097410172.99261.830110193.19281.276610203.29283.793910233.55286.4378
 10243.6294.7657 10263.7308.153910273.75313.925610283.79318.440610319.25339.2541
#Mann= 3 , 0 , 0
9680.753    0.04       09680.753    0.04       010319.25    0.04       0
#XS Ineff= 2 , 0
       0                               0
Bank Sta=9680.753,10319.25
Exp/Cntr=0.3,0.1

Type RM Length L Ch R = 1 ,14345.78,104.306200,104.306200,104.306200
XS GIS Cut Line= 3
871163.081931829788712.143650949871111.197345942 788669.98742494
870937.383983374788647.936475962
#Sta/Elev= 28
9877.753228.28129889.081 226.6939901.051224.03719904.939222.91839920.797215.3365
 9926.82211.95129936.655206.02929939.705205.63899944.604205.31869950.851204.7909
9960.932203.26529971.012 202.2849981.092201.73249984.232199.74319991.172194.5919
10001.25182.389610011.33191.495710021.41203.485110031.49212.378810041.57219.1688
10051.65222.827710061.73226.125910071.81229.199610081.89 232.72510091.97236.5109
10102.05240.676310112.13245.015210119.81247.0686
#Mann= 3 , 0 , 0
9877.753    0.05       09877.753    0.05       010119.81    0.05       0
#XS Ineff= 2 , 0
       0                               0
Bank Sta=9877.753,10119.81
Exp/Cntr=0.3,0.1

Type RM Length L Ch R = 1 ,14241.47,244.216600,244.216600,244.216600
XS GIS Cut Line= 2
871330.858375162788594.053949088 870837.80281961788531.553949088
#Sta/Elev= 30
9748.809225.79729795.035219.36539820.806 214.9949865.595210.91419875.675211.7392
9895.835210.97219915.995204.50889936.155194.14959946.235190.37079966.395186.0449
9996.635175.538410006.72175.4071 10016.8179.452710036.96191.865710047.04201.1057
10057.12 203.633 10067.2204.714210077.28208.967910087.36216.952610097.44222.6046
10107.52226.455410137.76241.650610147.84244.873610178.08245.687510188.16249.5156
10198.24249.138710208.32249.8611 10218.4259.170610238.56263.024710245.81270.2753
#Mann= 3 , 0 , 0
9748.809    0.06       09748.809    0.06       010245.81    0.06       0
#XS Ineff= 2 , 0
       0                               0
Bank Sta=9748.809,10245.81
Exp/Cntr=0.3,0.1

Type RM Length L Ch R = 1 ,13997.26,206.026900,206.026900,206.026900
XS GIS Cut Line= 6
 871407.22004383788407.803848348871228.360953718788363.179125185
871048.052486781788305.560492932870983.699902667788288.505081932
870875.410501851788271.459804852870778.211087383788267.241826415
#Sta/Elev= 30
9676.363221.22739812.477222.48699843.512218.37389853.857213.88619864.234211.9057
9924.055207.4926 9926.87206.92359937.416200.77619969.063179.05059979.613175.1764
 10000.7170.259310011.21172.370810021.72 181.78610032.23192.977310053.19208.9045
10063.54213.496210073.88215.424610115.26218.682710125.47220.841210135.65227.0877
10166.19229.568510196.47235.579110206.55239.649510216.63246.9977 10226.7252.9562
10236.72253.441110286.81261.181110296.81261.716110316.82259.513210323.61 259.568
#Mann= 3 , 0 , 0
9676.363    0.12       09676.363    0.12       010323.61    0.12       0
#XS Ineff= 2 , 0
       0                               0
Bank Sta=9676.363,10323.61
Exp/Cntr=0.3,0.1

Type RM Length L Ch R = 1 ,13791.23,206.027000,206.027000,206.027000
XS GIS Cut Line= 6
871563.582023906788260.338375602871338.876224575  788204.4561871
871130.537075307788108.637072668871066.133528199788087.646219545
870968.470998424788081.376131825870795.597689737788105.516883884
#Sta/Elev= 30
9599.046231.64849607.816225.71189628.255221.62489679.351 220.009 9877.65217.9622
9888.505217.12459899.408212.9744 9910.31 206.4249921.213198.84689943.579190.2671
9954.779185.24369965.979178.42399977.179174.16749988.379172.41269999.584  168.77
 10021.9172.859110055.34174.945110076.94177.205510087.64179.279810129.29191.9075
10169.69 200.45810209.69212.974210229.71216.929410259.86219.341410290.01217.9098
 10310.2218.562510320.34217.429210350.77216.598310360.91217.601710400.87225.3794
#Mann= 3 , 0 , 0
9599.046    0.12       09599.046    0.12       010400.87    0.12       0
#XS Ineff= 2 , 0
       0                               0
Bank Sta=9599.046,10400.87
Exp/Cntr=0.3,0.1

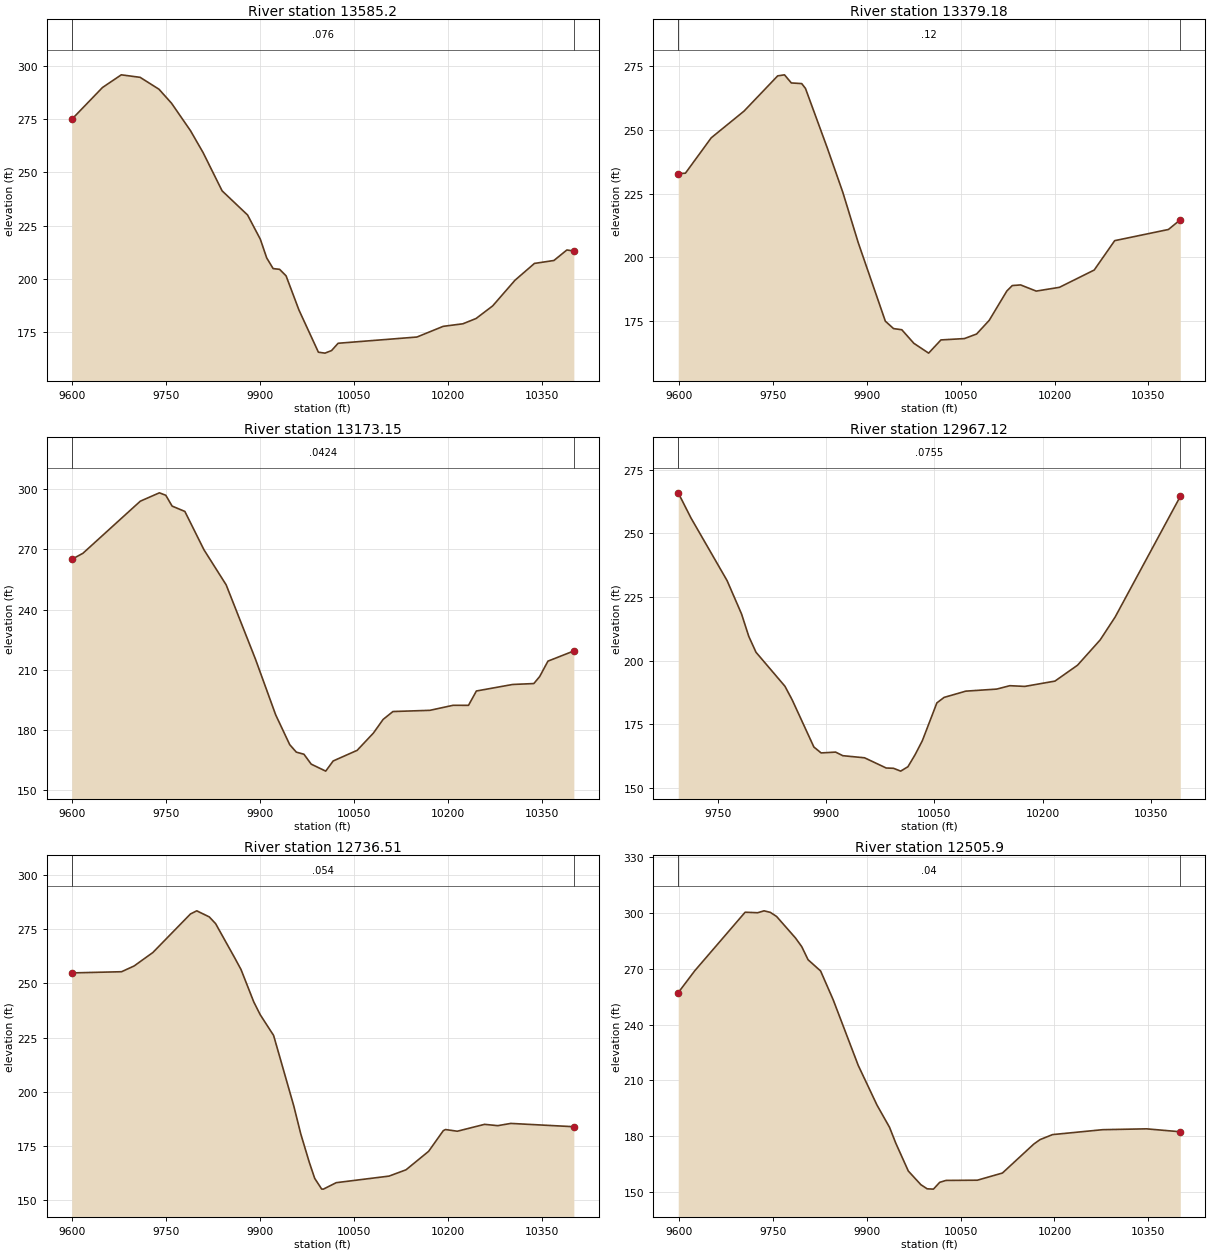
Type RM Length L Ch R = 1 , 13585.2,206.026900,206.026900,206.026900
XS GIS Cut Line= 6
871643.973214865787886.246447799871476.126147247787898.190559921
871330.816548274787922.193017429871256.131272022787941.415784391
871013.150380943788018.553708816870864.252704456788058.828367026
#Sta/Elev= 30
9599.042 274.9529648.086289.91859678.129295.87939708.216294.69919738.346 289.109
9758.433282.51949788.669269.62819808.857259.31189839.138 241.3769879.869230.0042
9900.234218.62099910.416209.82959920.682204.82649931.008204.47619941.334201.4268
9961.986185.31329992.985165.531210003.51165.0999   10014166.308910024.49169.7363
10150.37172.664910192.34177.689110223.81178.885510244.79181.365310271.42187.3161
10306.97199.348310338.05207.253110369.12208.629710389.84213.568110400.98213.0683
#Mann= 3 , 0 , 0
9599.042   0.076       09599.042   0.076       010400.98   0.076       0
#XS Ineff= 2 , 0
       0                               0
Bank Sta=9599.042,10400.98
Exp/Cntr=0.3,0.1

Type RM Length L Ch R = 1 ,13379.18,206.027000,206.027000,206.027000
XS GIS Cut Line= 6
871426.172661586787621.147995211871303.191645838787656.527327317
871207.017044099787703.917232425871135.849363598787762.992901408
 870988.16936047787935.261422474870767.086027685788040.643395365
#Sta/Elev= 30
9599.146232.78639610.653232.98959651.851  246.899704.284257.39399757.915 271.224
9768.814271.63899779.713268.4499 9796.33268.19259802.363266.27959837.072242.9621
9861.943 225.4919886.491205.74559929.862174.82039943.004171.90599956.146171.4621
9975.385166.1303    9999162.266910018.65167.454210056.15167.986810075.58169.7811
10095.69175.135910123.94186.699110132.58188.822710145.82189.071410170.82186.6473
10207.85188.1267 10263.4194.922410296.11206.468510381.89 210.85610400.89214.6767
#Mann= 3 , 0 , 0
9599.146    0.12       09599.146    0.12       010400.89    0.12       0
#XS Ineff= 2 , 0
       0                               0
Bank Sta=9599.146,10400.89
Exp/Cntr=0.3,0.1

Type RM Length L Ch R = 1 ,13173.15,206.026900,206.026900,206.026900
XS GIS Cut Line= 6
871352.541417309787550.333390488871110.181393284787595.741355774
871032.480398362787620.949595179870948.859061058787668.826533562
870780.261269142 787801.49581724870637.459089471787878.488884792
#Sta/Elev= 30
9599.063265.09479616.909268.12089708.475294.06199738.997298.23479749.171297.0205
9759.345291.62629779.693288.95939810.215269.8502 9845.64252.38749892.507215.3118
9924.735 187.6229947.184172.75079957.708169.04129969.867167.99229981.435163.0723
10004.64159.582410016.55164.646610054.83169.938510080.78178.535710096.32185.3438
10112.01189.273410171.01189.870610208.01192.375110232.67192.364810245.28199.5057
10303.11202.7517   10337 203.21110346.32206.690810359.54214.376710400.91219.4574
#Mann= 3 , 0 , 0
9599.063  0.0424       09599.063  0.0424       010400.91  0.0424       0
#XS Ineff= 2 , 0
       0                               0
Bank Sta=9599.063,10400.91
Exp/Cntr=0.3,0.1

Type RM Length L Ch R = 1 ,12967.12,230.612700,230.612700,230.612700
XS GIS Cut Line= 3
871122.525041848787541.970615774870685.025041848787514.192837983
870438.497264087787587.109504655
#Sta/Elev= 30
9695.155 265.9719712.715256.13739762.816231.47689782.856218.36829792.876209.5563
9802.896203.31349842.977189.95939852.997184.61049883.057166.07829893.077163.7564
9913.118164.08079923.138162.67299953.198161.84789983.259157.82839993.279157.7237
 10003.3156.604410013.32158.333810023.34163.100810033.36 168.608 10053.4183.4135
10063.42185.577210093.48188.036410136.38188.845210154.42190.176910175.27189.9006
10216.99191.982310248.27198.237210279.56208.144610300.41217.188210390.62264.5724
#Mann= 3 , 0 , 0
9695.155  0.0755       09695.155  0.0755       010390.62  0.0755       0
#XS Ineff= 2 , 0
       0                               0
Bank Sta=9695.155,10390.62
Exp/Cntr=0.3,0.1

Type RM Length L Ch R = 1 ,12736.51,230.612800,230.612800,230.612800
XS GIS Cut Line= 6
871404.218239292787460.579859827871220.577099612787470.929810785
871108.139138398787455.845905363871003.910293572787410.486337446
870824.693442154787291.379215768870655.847917823787250.872021321
#Sta/Elev= 30
9599.119254.75799678.623255.30519698.684257.94849728.693264.16859788.718281.9073
9798.732283.33879818.759280.53139828.823277.44379859.164261.76849869.383256.3314
9889.821241.36579900.168235.46349921.418225.98749953.625193.54629964.772180.6867
9978.338 167.6589987.065160.18419998.212155.2458   10001 155.22610021.38 158.191
10105.83161.225810132.89164.120910169.04172.639710192.43182.150510195.95182.6571
10214.81181.880610258.32 185.04610279.41184.445210300.25185.473610400.89183.9539
#Mann= 3 , 0 , 0
9599.119   0.054       09599.119   0.054       010400.89   0.054       0
#XS Ineff= 2 , 0
       0                               0
Bank Sta=9599.119,10400.89
Exp/Cntr=0.3,0.1

Type RM Length L Ch R = 1 , 12505.9,230.612800,230.612800,230.612800
XS GIS Cut Line= 6
871451.238210311787165.003145248871268.191881962787184.577897465
871142.073146223787192.117476743870803.087981746787178.113443022
870721.671486125787178.347996301870651.081563921787182.459612981
#Sta/Elev= 30
9599.028257.06649625.415268.81839705.872300.21029725.986299.94019736.043300.9631
  9746.1300.13799756.157297.92689786.319286.39479796.347281.73379806.376274.7459
9826.433268.70099846.491253.28769886.529218.07449916.552196.74869936.553184.8581
9946.554176.33469966.556161.41169986.602154.09269996.628151.886710006.65151.7168
10016.68155.3626 10026.7156.383810076.83156.501610116.87160.353910166.89175.8653
 10176.9178.277810196.91180.957810276.93183.594510346.96184.047210400.97182.4753
#Mann= 3 , 0 , 0
9599.028    0.04       09599.028    0.04       010400.97    0.04       0
#XS Ineff= 2 , 0
       0                               0
Bank Sta=9599.028,10400.97
Exp/Cntr=0.3,0.1