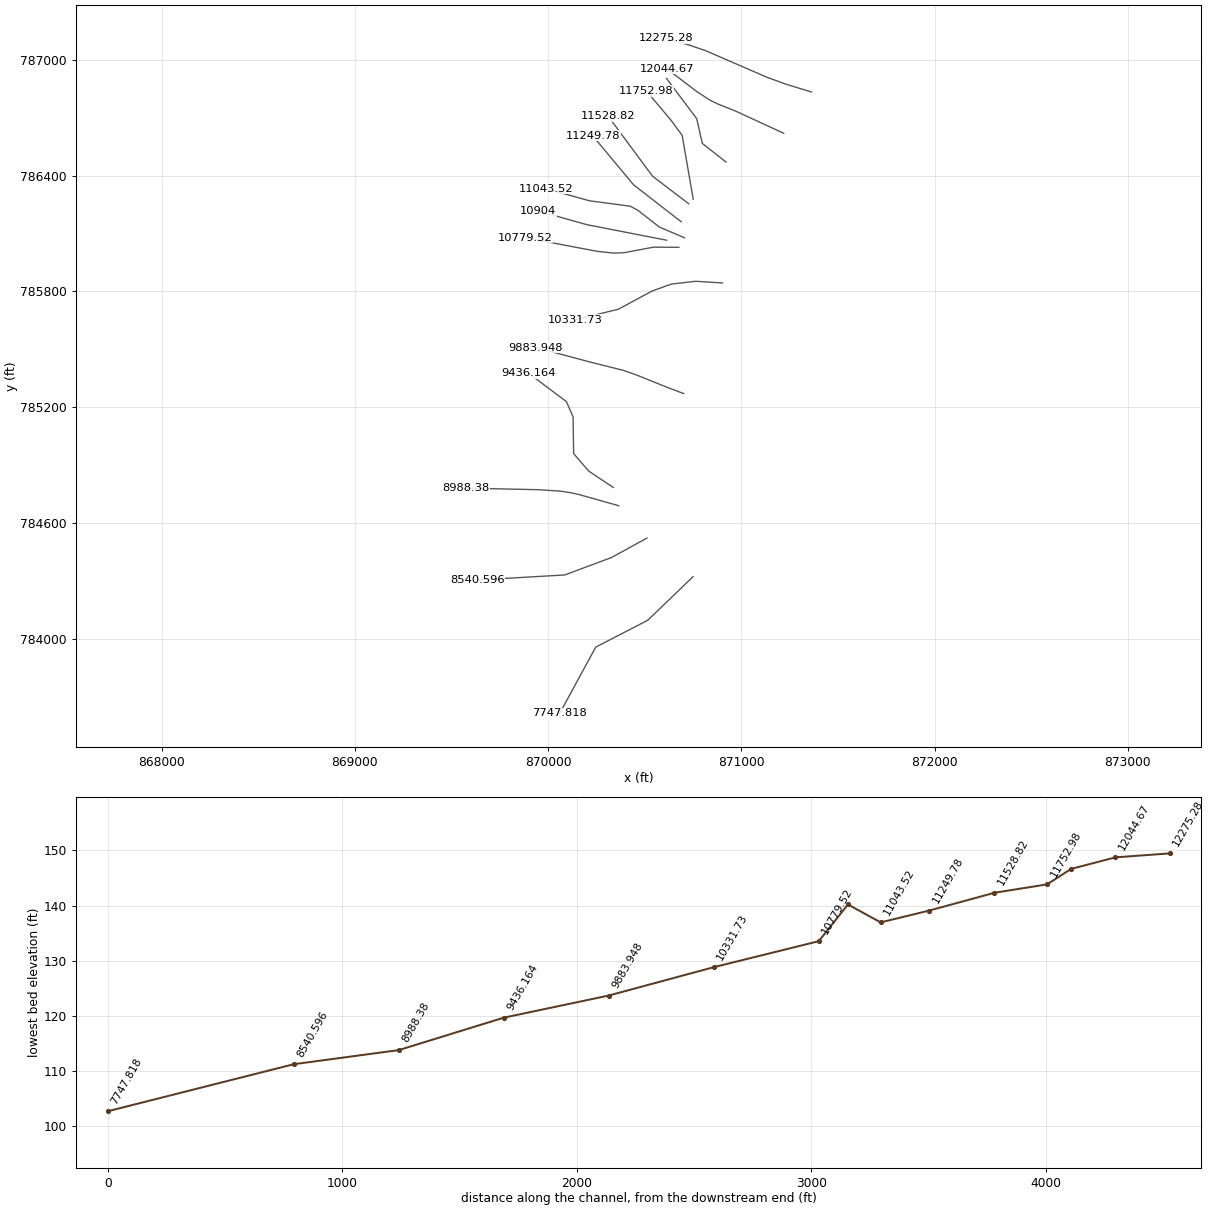
HEC-RAS study 11677_ras.prj: 11677

--- 11677_ras.g01 (geometry) --- (continued)

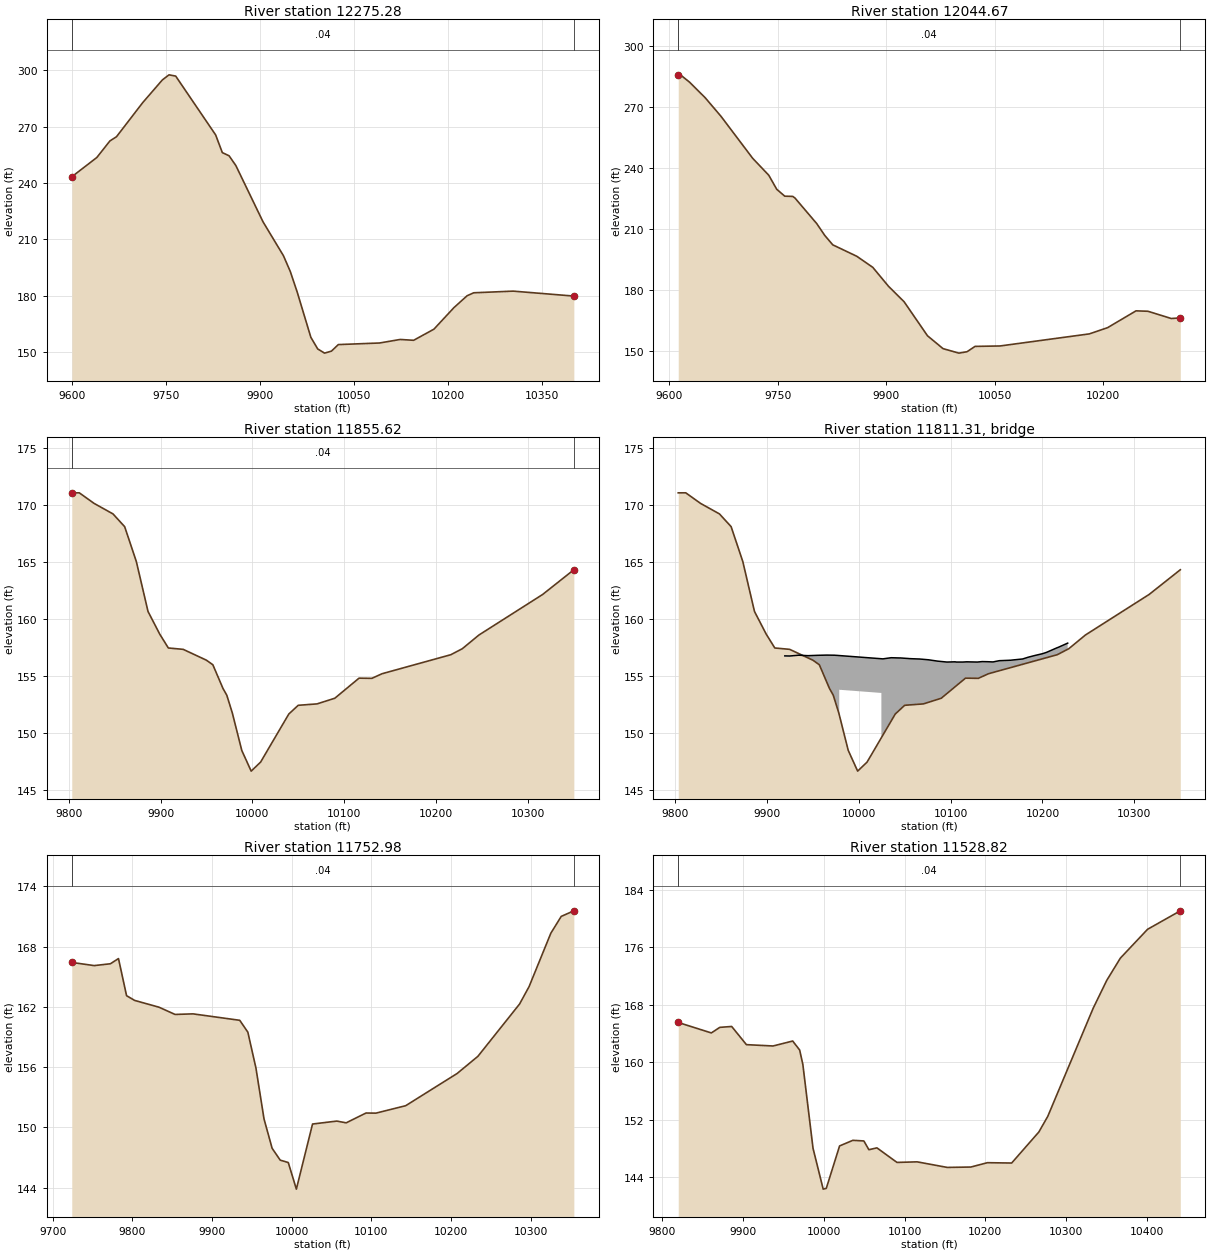
Type RM Length L Ch R = 1 ,12275.28,230.612700,230.612700,230.612700
XS GIS Cut Line= 6
871363.303888751786832.108862478871233.607792228786871.533736191
871132.510595081786908.305301063870815.994066429787045.553501228
870734.257871608 787073.59817814870612.136275437787109.731093806
#Sta/Elev= 30
9599.035243.32939639.069253.60579659.973262.42949670.425264.64289712.232282.7651
 9743.75294.90559754.391 297.6159765.032296.94289828.878265.60989839.518256.2046
9850.308254.51829861.147 249.3089904.501219.37649937.106201.33869948.061192.9383
9959.015182.06839980.925157.87189991.879151.691510002.83149.460910013.82150.5276
 10024.8154.0076 10090.7154.855810123.52156.732410145.11156.293410177.49  162.21
 10209.4173.659210230.55180.024510241.12181.585610304.13182.464210400.98179.8324
#Mann= 3 , 0 , 0
9599.035    0.04       09599.035    0.04       010400.98    0.04       0
#XS Ineff= 2 , 0
       0                               0
Bank Sta=9599.035,10400.98
Exp/Cntr=0.3,0.1

Type RM Length L Ch R = 1 ,12044.67,189.046900,189.046900,189.046900
XS GIS Cut Line= 6
871219.257806476786618.514896081 870969.24107515786733.738953799
870878.291031292786769.977453851870836.478572281786790.569942505
870767.795779126786835.469637277870615.100190008786952.186819758
#Sta/Elev= 30
9612.589285.68359617.234285.20559628.142282.10769649.959274.37359671.775265.2361
9715.597244.56949737.723236.29249748.785229.35999759.848225.97229770.911225.8611
9773.943225.07939804.099 212.4699815.162206.66279826.224202.02899859.413196.4095
9881.538190.95979903.268181.64029924.839174.02899957.194157.28729978.622150.9653
10000.63148.743610011.78149.422310022.93152.056710057.51152.266810180.97158.2093
10206.15161.268910245.48169.546910261.95169.343610294.25165.775210306.71166.0714
#Mann= 3 , 0 , 0
9612.589    0.04       09612.589    0.04       010306.71    0.04       0
#XS Ineff= 2 , 0
       0                10135.36       0
Bank Sta=9612.589,10306.71
Exp/Cntr=0.3,0.1

Type RM Length L Ch R = 1 ,11855.62,102.649300,102.649300,102.649300
XS GIS Cut Line= 4
870920.268097401786469.922004655870797.872264087786566.276171312
870769.226430714786693.880337983870612.976430744786902.213671312
#Sta/Elev= 30
9803.205171.06519811.415171.06579827.581170.13569848.091169.21729860.818168.0989
9873.545165.03769886.271 160.6599898.998158.67599908.414157.45329924.581157.3339
9949.906156.38249956.914155.98079967.918153.9084 9972.09153.31139978.167151.7382
9988.416148.46719998.665146.650310008.91147.440910039.66151.660710049.91152.4249
10070.41152.548910089.76153.044810116.16154.806710130.13154.789710141.16155.1932
10216.16156.863710228.66157.3887 10246.8158.592210316.16162.147310350.17164.3167
#Mann= 3 , 0 , 0
9803.205    0.04       09803.205    0.04       010350.17    0.04       0
#XS Ineff= 2 , 0
       0                10054.94       0
Bank Sta=9803.205,10350.17
Exp/Cntr=0.3,0.1

Type RM Length L Ch R = 3 ,11811.31,,,
BEGIN DESCRIPTION:
END DESCRIPTION:
Bridge Culvert--1,0,-1,-1, 0
Deck Dist Width WeirC Skew NumUp NumDn MinLoCord MaxHiCord MaxSubmerge Is_Ogee
37.544650,27.560000,2.6,0, 41, 41, , , 0.95, 0, 0,0,,
 9919.34 9924.47 9934.54 9944.61 9954.69 9964.76 9973.50 9978.61 9978.6110024.54
10024.5410026.1910035.2510043.6610045.3310055.4510064.7110065.5610075.6810085.80
10095.9110104.7610106.1810113.1210117.5310128.8710134.3010140.2210146.1210152.36
10153.0210165.3810168.6410178.4010184.2610191.4110199.8810204.4310215.5010217.45
10227.48
  156.76  156.75  156.82  156.78  156.81  156.83  156.82  156.79  156.79  156.51
  156.51  156.50  156.60  156.58  156.58  156.52  156.49  156.49  156.42  156.30
  156.22  156.24  156.22  156.22  156.24  156.22  156.26  156.25  156.23  156.33
  156.34  156.38  156.41  156.49  156.64  156.79  156.95  157.07  157.46  157.52
  157.88
 -843.24 -843.25 -843.18 -843.22 -843.19 -843.17 -843.18 -843.21  153.79  153.51
 -843.49 -843.50 -843.40 -843.42 -843.42 -843.48 -843.51 -843.51 -843.58 -843.70
 -843.78 -843.76 -843.78 -843.78 -843.76 -843.78 -843.74 -843.75 -843.77 -843.67
 -843.66 -843.62 -843.59 -843.51 -843.36 -843.21 -843.05 -842.93 -842.54 -842.48
 -842.12
 9919.34 9924.47 9934.54 9944.61 9954.69 9964.76 9973.34 9973.34 9973.5010019.27
10019.2710026.1910035.2510043.6610045.3310055.4510064.7110065.5610075.6810085.80
10095.9110104.7610106.1810113.1210117.5310128.8710134.3010140.2210146.1210152.36
10153.0210165.3810168.6410178.4010184.2610191.4110199.8810204.4310215.5010217.45
10227.48
  156.76  156.75  156.82  156.78  156.81  156.83  156.82  156.82  156.82  156.54
  156.54  156.50  156.60  156.58  156.58  156.52  156.49  156.49  156.42  156.30
  156.22  156.24  156.22  156.22  156.24  156.22  156.26  156.25  156.23  156.33
  156.34  156.38  156.41  156.49  156.64  156.79  156.95  157.07  157.46  157.52
  157.88
 -843.24 -843.25 -843.18 -843.22 -843.19 -843.17 -843.18  153.82  153.82  153.54
 -843.46 -843.50 -843.40 -843.42 -843.42 -843.48 -843.51 -843.51 -843.58 -843.70
 -843.78 -843.76 -843.78 -843.78 -843.76 -843.78 -843.74 -843.75 -843.77 -843.67
 -843.66 -843.62 -843.59 -843.51 -843.36 -843.21 -843.05 -842.93 -842.54 -842.48
 -842.12
BR Coef=-1 , 0 , 0 ,, 0 ,,,0.8,0,1,0,
WSPro=,,,, 1 ,,,, 0 ,,,, 0 ,,,,-1 ,-1 ,-1 , 0 , 0 , 0 , 0 , 0
BC Design=,, 0 ,, 0 ,,,,,,

Type RM Length L Ch R = 1 ,11752.98,224.156600,224.156600,224.156600
XS GIS Cut Line= 5
870750.997264087786277.213671327870717.143097401786472.526171312
870693.705597371786607.942837983870633.809764057 786688.67200467
870508.809764057 786837.10950467
#Sta/Elev= 30
9723.967166.42199752.168166.10679772.466166.28979782.615 166.8069792.764163.1095
9802.913 162.638 9833.36161.96579853.659161.24129876.188161.29869934.851160.6569
    9945 159.4749955.148155.90599965.297150.83469975.446147.91279985.594146.7315
9995.743146.490410005.89143.841910026.19150.326210056.64150.619110068.41150.4454
10093.31151.422210105.76151.411410143.12152.151210207.64155.357110233.78157.0707
10286.08162.279710298.02164.0151 10325.3 169.32810338.37171.0085 10354.2171.5623
#Mann= 3 , 0 , 0
9723.967    0.04       09723.967    0.04       0 10354.2    0.04       0
#XS Ineff= 2 , 0
       0                 10049.9       0
Bank Sta=9723.967,10354.2
Exp/Cntr=0.3,0.1

Type RM Length L Ch R = 1 ,11528.82,279.042400,279.042400,279.042400
XS GIS Cut Line= 3
870727.559764057786253.776171327870540.059764057786397.005337983
870310.893097401786706.901171312
#Sta/Elev= 30
 9819.91165.51199860.882164.05689871.346164.8318 9886.05164.95629904.293162.4274
9937.239162.24169961.553162.93039970.186161.68299974.137159.67459986.721148.0138
9999.304142.326410003.13142.433310019.61148.336310036.08 149.11710049.64149.0293
10055.86147.8092 10065.8148.067410090.67146.040810115.55146.121910152.86145.3469
 10182.1145.400210202.61146.004310232.55 145.95710266.19150.271110277.23152.4463
10333.46167.495510350.28171.3747 10367.1174.465210400.74178.474310441.28181.0452
#Mann= 3 , 0 , 0
 9819.91    0.04       0 9819.91    0.04       010441.28    0.04       0
#XS Ineff= 2 , 0
       0                               0
Bank Sta=9819.91,10441.28
Exp/Cntr=0.3,0.1

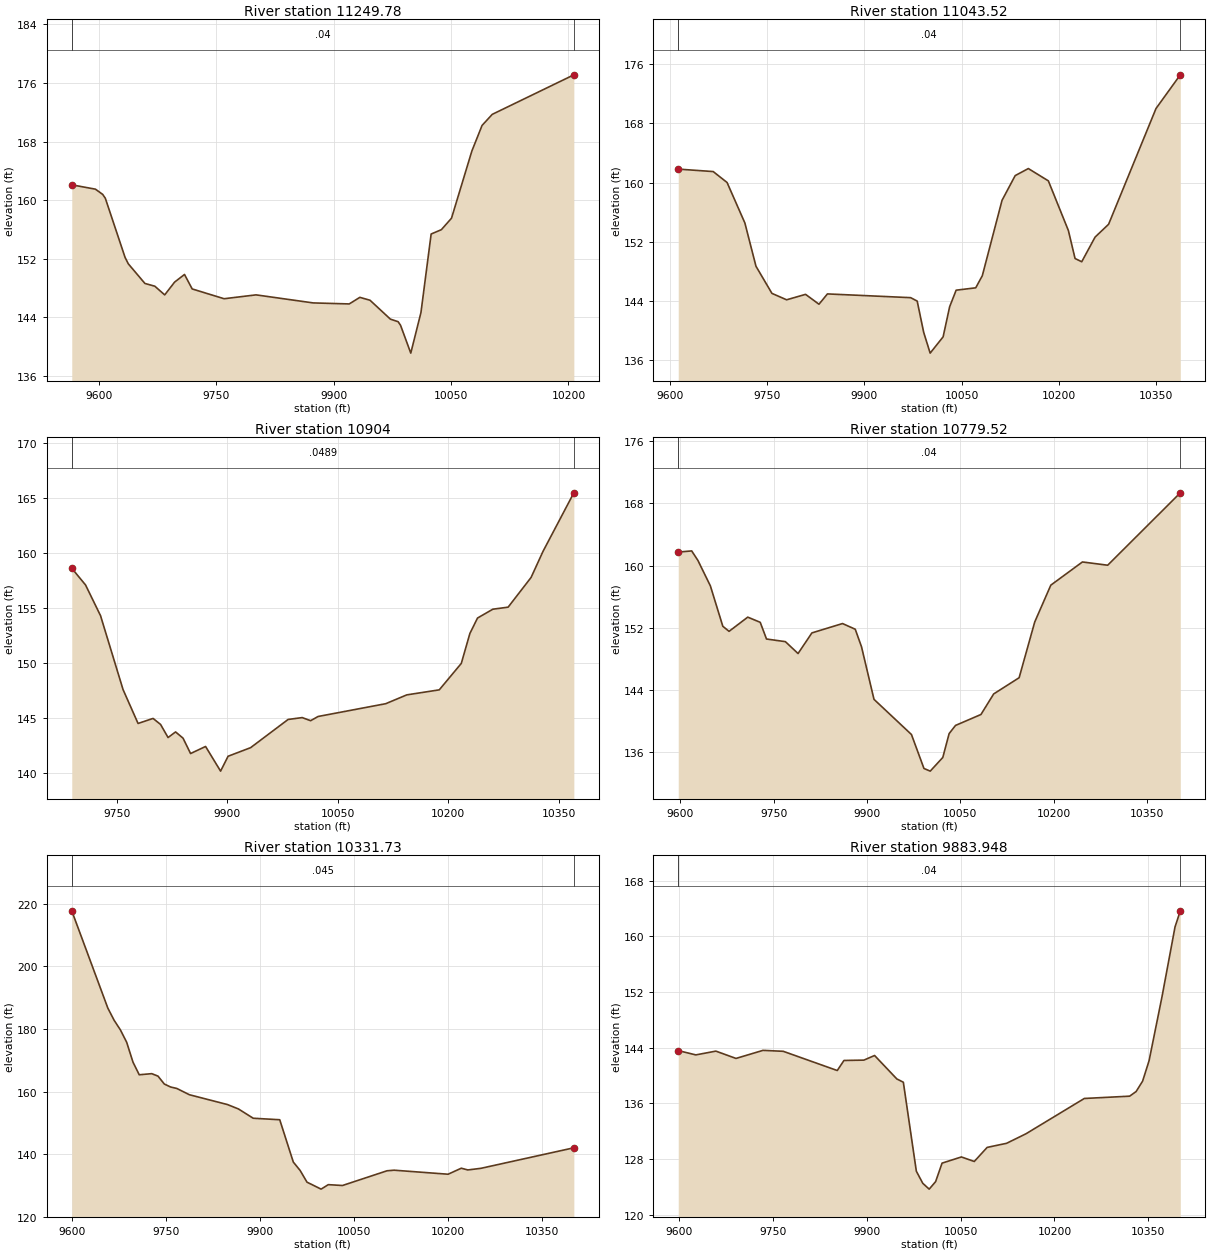
Type RM Length L Ch R = 1 ,11249.78,206.260100,206.260100,206.260100
XS GIS Cut Line= 3
870688.895410061 786160.75990206870442.291040212786351.822747171
870231.233246207786605.092099965
#Sta/Elev= 30
9565.245162.08429595.473161.49119604.823160.76889608.123160.24959633.424152.1494
9637.478151.29259658.724148.60669671.374148.23139684.024147.04419696.675 148.792
9709.325149.83459719.116147.85789759.926146.52039800.754147.04729873.777145.9478
9919.834145.80759933.409146.70859946.426146.3116 9972.46143.72969982.316 143.381
9985.477142.87779998.494139.086710011.51144.638910024.53155.364110037.55155.9502
10050.56157.5247 10076.6166.714210089.61170.201910102.63171.713210206.89 177.114
#Mann= 3 , 0 , 0
9565.245    0.04       09565.245    0.04       010206.89    0.04       0
#XS Ineff= 2 , 0
       0                               0
Bank Sta=9565.245,10206.89
Exp/Cntr=0.3,0.1

Type RM Length L Ch R = 1 ,11043.52,139.516600,139.516600,139.516600
XS GIS Cut Line= 6
870705.888061869786077.893538594870576.104998783786133.140280566
870465.345013506786219.499243098870425.516140468786241.155621335
870214.610766854786269.088349176869989.153168388786332.022287872
#Sta/Elev= 30
9612.638161.81169666.592161.48019687.982 160.0069715.492154.53359732.596148.6938
9757.231145.02539779.878144.15699809.132144.89259829.848143.55939842.883144.9526
9971.349144.44529981.407143.98159991.416139.767710001.42136.953610021.43139.1541
10031.47143.214510041.52145.455310071.75145.7767 10081.9147.410710112.33 157.592
10132.62 160.93310152.91161.887310183.82160.224110214.73 153.51510225.04149.7341
10235.34149.296510255.95152.6285 10276.8154.360510349.99170.003310387.46 174.548
#Mann= 3 , 0 , 0
9612.638    0.04       09612.638    0.04       010387.46    0.04       0
#XS Ineff= 2 , 0
       0                               0
Bank Sta=9612.638,10387.46
Exp/Cntr=0.3,0.1

Type RM Length L Ch R = 1 ,   10904,124.483400,124.483400,124.483400
XS GIS Cut Line= 3
870613.358936429786065.228479519870202.351653337786145.208275124
869949.082300544786216.301426783
#Sta/Elev= 30
9688.731 158.6319707.434157.11499727.809154.32169758.372147.60799778.747144.5303
9799.122144.9863 9809.31144.44089819.497143.25129829.685 143.7619839.873143.1886
 9850.06141.79639870.435142.43829890.811140.19849900.998141.54979931.561142.3294
9982.499144.892410001.65145.062910013.06144.781210023.25145.163310115.08146.3256
10143.68147.127310187.79147.583610217.68149.984610229.33152.703810239.72154.1087
10260.49154.910110281.27155.097310312.43157.794810328.69160.171410370.51165.4857
#Mann= 3 , 0 , 0
9688.731  0.0489       09688.731  0.0489       010370.51  0.0489       0
#XS Ineff= 2 , 0
       0                               0
Bank Sta=9688.731,10370.51
Exp/Cntr=0.3,0.1

Type RM Length L Ch R = 1 ,10779.52,447.784000,447.784000,447.784000
XS GIS Cut Line= 6
870676.540394666786028.435929502870545.526627553786029.199049744
 870392.72541433786000.477903811870336.569383548785998.532535744
870252.916136324786007.919893412869880.057811661786078.521180423
#Sta/Elev= 30
 9596.66161.74319618.269161.89449628.293160.66899648.299157.39489668.306152.1929
9678.309151.5385 9708.36153.36769728.399152.70179738.503150.55119768.817150.2128
9789.187148.68229811.448151.33879860.657152.54339881.078151.80929891.155149.5519
 9911.23142.78119971.402138.25679991.505133.881510001.56133.541810021.76135.2981
10031.95138.376110042.18 139.42410083.07140.832710103.52  143.4810144.41145.5669
10169.48152.744510195.34157.4873 10246.1160.471910286.71 160.053 10403.4169.3736
#Mann= 3 , 0 , 0
 9596.66    0.04       0 9596.66    0.04       0 10403.4    0.04       0
#XS Ineff= 2 , 0
       0                               0
Bank Sta=9596.66,10403.4
Exp/Cntr=0.3,0.1

Type RM Length L Ch R = 1 ,10331.73,447.784000,447.784000,447.784000
XS GIS Cut Line= 6
870902.398593588785844.036187949870763.680003945785852.770305647
870637.757593576785838.269431835870538.557919011785802.451931086
870363.415706081785707.906160756870139.749927431785653.401618576
#Sta/Elev= 30
9599.146217.7638 9656.77186.66739666.809182.78799676.849179.70359686.875175.7403
9696.878169.42459706.881165.37169726.886165.72889736.889164.93489746.905162.4196
9756.922161.46939766.939160.99789786.974158.99639847.667155.86289865.171154.4652
9888.927151.48299931.266151.00219952.957137.47019963.802134.80229974.796131.0558
9997.322128.8302 10008.8130.259710031.44129.986310102.56134.6885 10113.9134.8796
10200.14133.592210221.18135.5121 10231.7134.960610252.47135.475610400.93142.0376
#Mann= 3 , 0 , 0
9599.146   0.045       09599.146   0.045       010400.93   0.045       0
#XS Ineff= 2 , 0
       0                               0
Bank Sta=9599.146,10400.93
Exp/Cntr=0.3,0.1

Type RM Length L Ch R = 1 ,9883.948,447.783900,447.783900,447.783900
XS GIS Cut Line= 6
870701.310962515785271.899973097870621.167195824785302.039261035
870458.978904933785367.437957978 870388.94439822785391.979585174
870221.736740087785433.749224584869936.842890853785509.828750033
#Sta/Elev= 30
9599.027143.57789627.137142.96379659.189143.50389691.301142.4545 9734.43 143.613
9766.777143.47769853.036 140.7189863.744142.16249895.533142.21119912.633142.8764
9948.217139.5082  9958.6139.03829979.353126.26669989.621124.52659999.886123.6893
10010.17124.769110020.45127.422510051.32128.308710071.89127.659210092.46129.6814
10123.43130.265510154.48131.635810247.64136.704910320.09137.036610330.44137.7051
10340.79139.198110351.14142.143210371.84151.354710392.54161.331810400.99163.6484
#Mann= 3 , 0 , 0
9599.027    0.04       09599.027    0.04       010400.99    0.04       0
#XS Ineff= 2 , 0
       0                               0
Bank Sta=9599.027,10400.99
Exp/Cntr=0.3,0.1

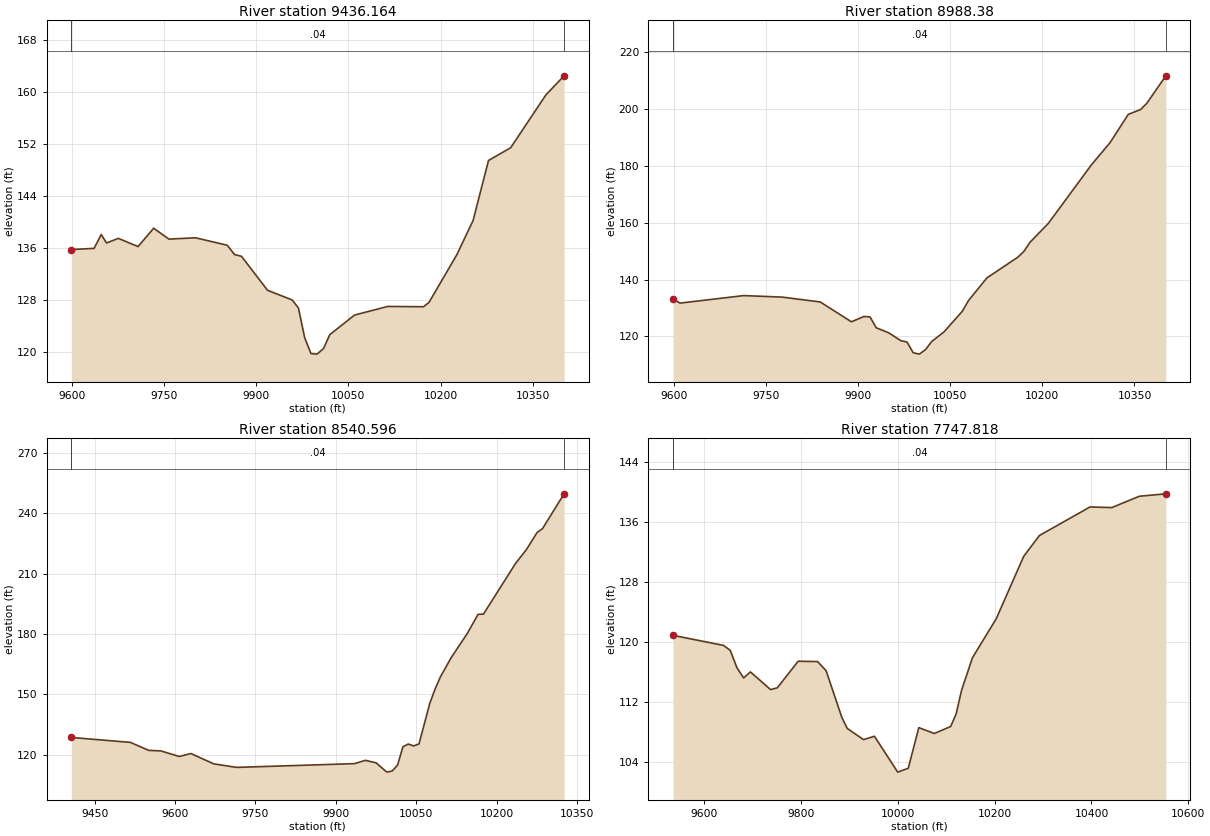
Type RM Length L Ch R = 1 ,9436.164,447.784000,447.784000,447.784000
XS GIS Cut Line= 6
870337.033976358784786.069113321 870210.53730102784870.504380784
870132.318663587784961.193622629870129.330391717785151.313759862
870094.979817433785230.155728813869898.714886918785377.296462792
#Sta/Elev= 30
9599.223135.78699636.335135.9702 9647.92138.10149656.522136.79329675.791137.5095
9707.802136.24199733.213139.07269758.033137.39349801.043137.60039852.851136.4529
 9864.63135.02649876.042134.74339918.473129.50849958.634128.01359968.666126.7808
9978.876122.18919989.086119.7574    9999119.671310009.48120.529110019.65122.6674
 10059.9125.686410113.88127.020310172.09126.971610181.12127.646310226.54135.0238
10252.73140.246610277.88149.512810313.88151.4692 10371.2 159.61110400.82 162.555
#Mann= 3 , 0 , 0
9599.223    0.04       09599.223    0.04       010400.82    0.04       0
#XS Ineff= 2 , 0
       0                               0
Bank Sta=9599.223,10400.82
Exp/Cntr=0.3,0.1

Type RM Length L Ch R = 1 , 8988.38,447.784000,447.784000,447.784000
XS GIS Cut Line= 6
870365.955901049784691.418796498870160.181920491784749.237605005
870114.943649468784759.113738762870062.501512861784766.958150414
869951.020589537784774.259390207 869573.98615672784782.405315337
#Sta/Elev= 30
9599.045133.1886 9610.37131.71789714.068134.35649776.547133.82679838.579132.1208
9889.385125.15189909.607127.01819919.663126.87239929.701123.05929949.777121.3165
9969.835118.5217 9979.85118.04799989.864114.28929999.879113.795210009.89115.3546
10019.89118.2163 10039.9121.575110069.91128.875810079.91132.612910109.92140.5845
10159.93147.803510169.93149.839610179.93153.060810209.94159.749410279.96180.2987
10309.96187.986710339.97198.021710359.97199.709910369.98 201.868   10401211.5508
#Mann= 3 , 0 , 0
9599.045    0.04       09599.045    0.04       0   10401    0.04       0
#XS Ineff= 2 , 0
       0                               0
Bank Sta=9599.045,10401
Exp/Cntr=0.3,0.1

Type RM Length L Ch R = 1 ,8540.596,792.778100,792.778100,792.778100
XS GIS Cut Line= 4
870511.473422468784524.119297773870329.330279201784423.894866213
870086.126200259784333.147075564869634.737311333784307.105408892
#Sta/Elev= 30
9406.317128.46959516.431126.03999550.673122.0643  9573.5121.79039607.742119.0116
9629.509120.47869672.203115.34049714.897113.58839935.025115.46049955.058 117.091
9975.091115.86479995.124111.234110005.14111.809510015.16114.703210025.17123.8322
10035.19125.213510045.21 124.26310055.22125.284910075.26145.420610085.27152.5947
10095.29158.687810115.32168.212810145.37180.224410165.41189.728910175.42189.8068
10235.52215.088510255.56 221.89110275.59230.427110285.61232.317410325.94249.6525
#Mann= 3 , 0 , 0
9406.317    0.04       09406.317    0.04       010325.94    0.04       0
#XS Ineff= 2 , 0
       09954.432                       0
Bank Sta=9406.317,10325.94
Exp/Cntr=0.3,0.1

Type RM Length L Ch R = 1 ,7747.818,655.837000,655.837000,655.837000
XS GIS Cut Line= 4
870750.188700259784324.466520011870515.813700259784098.772075564
 870246.71647802783959.883186668870060.084533572 783617.00124222
#Sta/Elev= 30
9535.105120.93329639.487119.5894 9653.37118.93819667.253116.60929681.136115.2569
9695.018116.06319736.666113.70929750.586113.93769793.836117.48349833.845117.4379
9851.503116.22659883.904110.02689895.157108.53419928.917 107.0419951.424107.4908
9999.526102.711110021.33103.228310043.13108.639710075.21107.857910108.97108.7894
10120.23110.446710131.48113.605110153.99117.945410203.02123.124210259.95131.4568
 10292.4134.230210396.99138.033510442.12137.952410499.04139.462910553.69139.7846
#Mann= 3 , 0 , 0
9535.105    0.04       09535.105    0.04       010553.69    0.04       0
#XS Ineff= 2 , 0
       0                               0
Bank Sta=9535.105,10553.69
Exp/Cntr=0.3,0.1