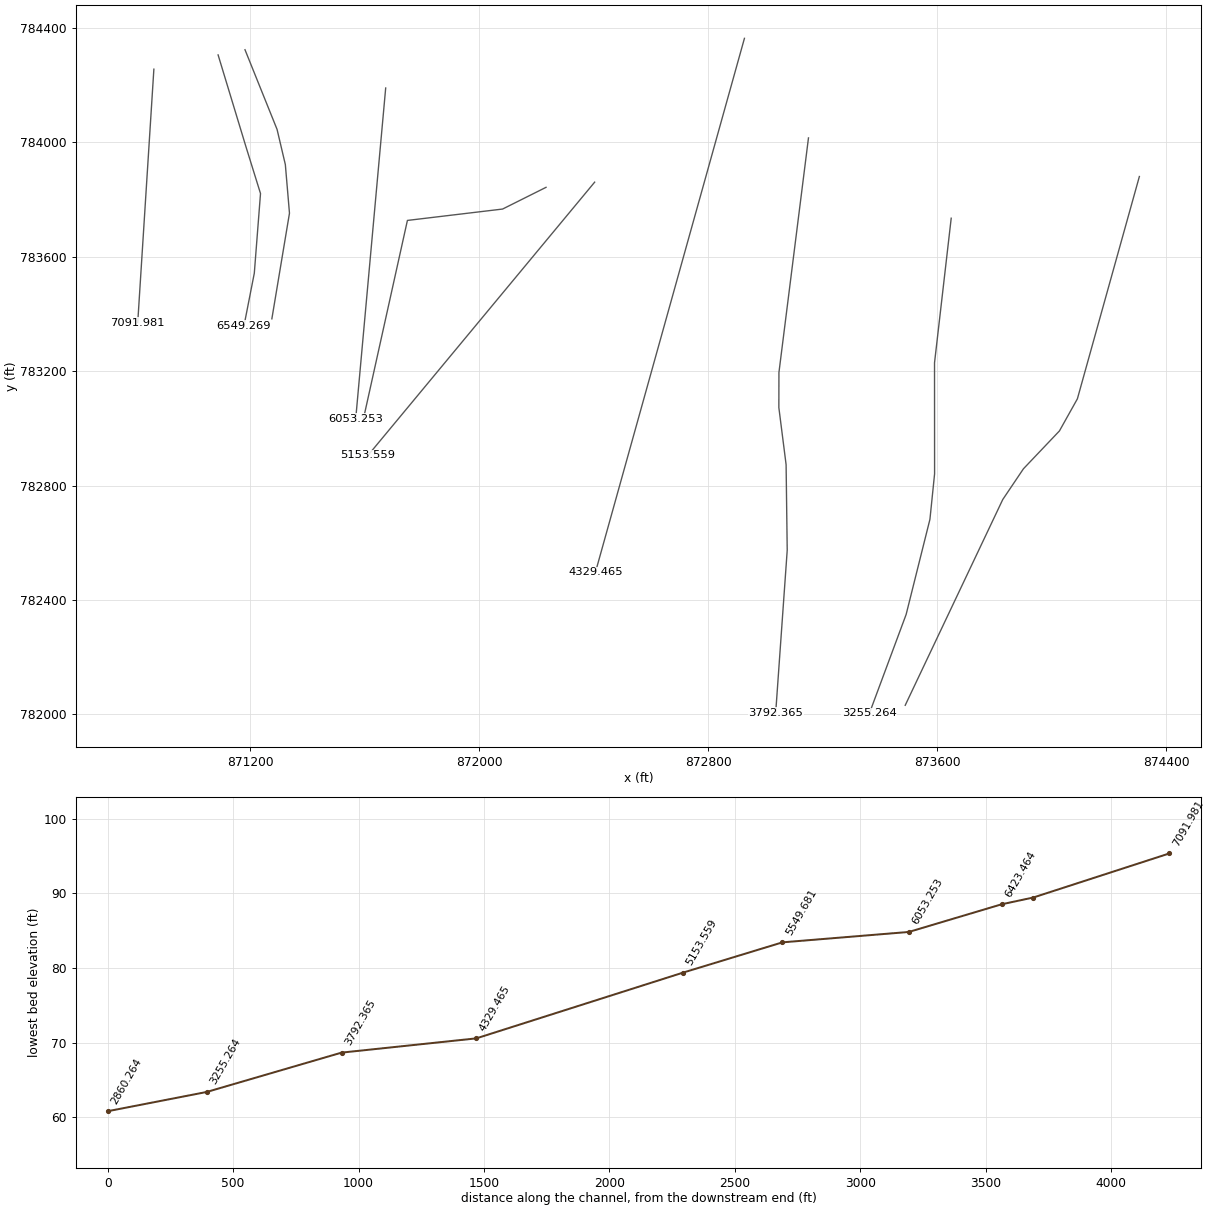
HEC-RAS study 11677_ras.prj: 11677

--- 11677_ras.g01 (geometry) --- (continued)

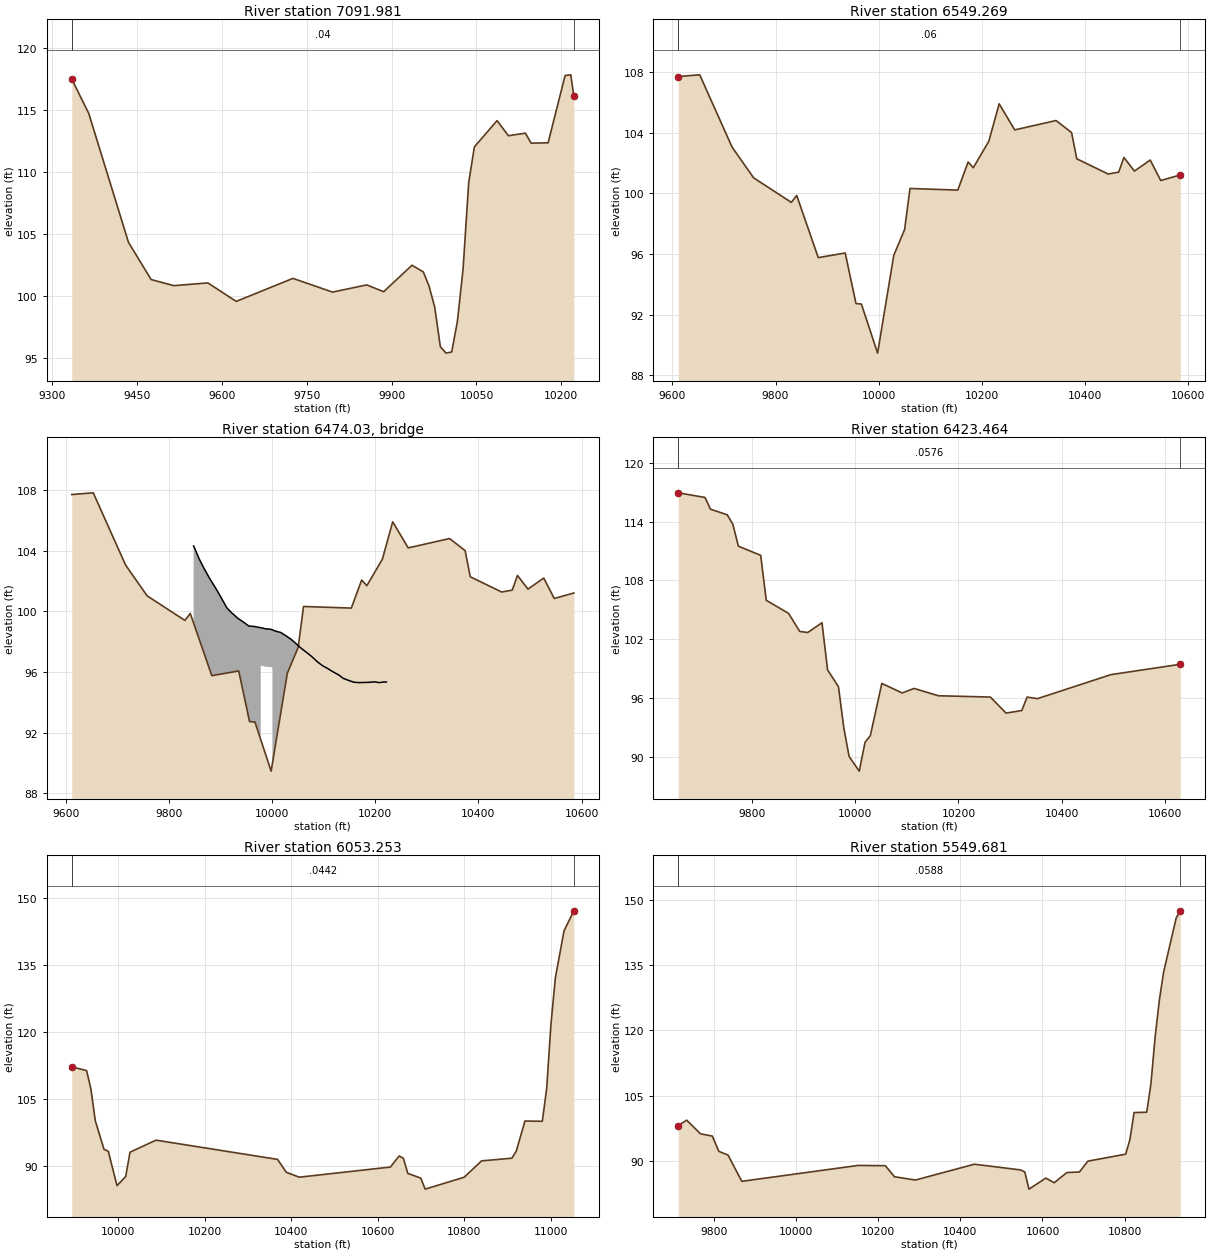
Type RM Length L Ch R = 1 ,7091.981,542.712500,542.712500,542.712500
XS GIS Cut Line= 2
870863.035922498784255.022075564870806.612311363783369.605408892
#Sta/Elev= 30
9334.874117.50399364.957114.71889435.099104.3166 9475.18101.31119515.262100.8229
9575.383101.04379625.48599.549989725.687101.40869795.829100.29939855.951100.8831
9886.012 100.3329936.113102.47119956.154101.92669966.174100.78759976.19599.09707
9986.21595.892759996.235 95.373610006.2695.4679610016.2897.92293 10026.3102.1356
10036.32109.144210046.34112.026810086.42114.145310106.46112.926610136.52113.1351
10146.54112.3278 10176.6112.352910206.66117.786810216.68117.843610222.09116.1126
#Mann= 3 , 0 , 0
9334.874    0.04       09334.874    0.04       010222.09    0.04       0
#XS Ineff= 2 , 0
       09579.866                       0
Bank Sta=9334.874,10222.09
Exp/Cntr=0.3,0.1

Type RM Length L Ch R = 1 ,6549.269,125.804600,125.804600,125.804600
XS GIS Cut Line= 5
871087.476832867784304.888688907871185.086501807 783983.13829878
871235.698922694783820.455517232871214.007885188783542.087202176
871177.856155932783357.713383108
#Sta/Elev= 30
9611.368107.72649653.052 107.8379715.752103.06579757.552101.03259830.70399.41154
9841.15399.868629882.95395.762149935.20396.067779956.12292.727069966.594 92.6951
9998.01389.4544810029.4395.9198710050.3897.6154410060.85100.329310153.54100.2238
 10173.6102.080410183.63101.701410213.72103.451810233.78105.922410263.87104.1995
10344.11 104.818 10374.2 104.02210384.23102.292110445.17101.284410465.55101.4098
10475.74102.378910496.12101.477310526.69 102.20810547.07100.857410585.07101.2213
#Mann= 3 , 0 , 0
9611.368    0.06       09611.368    0.06       010585.07    0.06       0
#XS Ineff= 2 , 0
       09877.313        10074.17       0
Bank Sta=9611.368,10585.07
Exp/Cntr=0.3,0.1

Type RM Length L Ch R = 3 , 6474.03,,,
BEGIN DESCRIPTION:
END DESCRIPTION:
Bridge Culvert--1,0,-1,-1, 0
Deck Dist Width WeirC Skew NumUp NumDn MinLoCord MaxHiCord MaxSubmerge Is_Ogee
44.367300,37.070000,2.6,0, 53, 53, , , 0.95, 0, 0,0,,
 9847.63 9848.32 9858.95 9866.43 9869.58 9880.21 9890.84 9895.91 9901.47 9912.10
 9922.73 9925.38 9933.36 9943.99 9954.62 9954.86 9965.25 9975.88 9977.85 9977.85
 9984.33 9986.51 9988.36 9996.7010000.8210000.8210006.8010016.9010027.0010037.09
10047.1910050.7310057.2910067.3810077.4810087.5810090.2510097.6510107.7210117.79
10127.8610129.4010137.9210147.9910158.0610168.1310178.2010188.2610198.3310208.40
10215.8310218.4710221.56
  104.33  104.28  103.44  102.94  102.74  102.10  101.52  101.23  100.89  100.24
   99.87   99.80   99.55   99.31   99.04   99.04   99.01   98.94   98.93   98.93
   98.88   98.85   98.85   98.83   98.78   98.78   98.70   98.61   98.39   98.15
   97.85   97.74   97.54   97.28   97.00   96.68   96.61   96.42   96.23   96.02
   95.83   95.80   95.58   95.45   95.33   95.30   95.31   95.32   95.35   95.30
   95.34   95.34   95.34
 -895.67 -895.72 -896.56 -897.06 -897.26 -897.90 -898.48 -898.77 -899.11 -899.76
 -900.13 -900.20 -900.45 -900.69 -900.96 -900.96 -900.99 -901.06 -901.07   96.43
   96.38   96.35   96.35   96.33   96.28 -901.22 -901.30 -901.39 -901.61 -901.85
 -902.15 -902.26 -902.46 -902.72 -903.00 -903.32 -903.39 -903.58 -903.77 -903.98
 -904.17 -904.20 -904.42 -904.55 -904.67 -904.70 -904.69 -904.68 -904.65 -904.70
 -904.66 -904.66 -904.66
 9847.63 9848.32 9858.95 9866.43 9869.58 9880.21 9890.84 9895.91 9901.47 9912.10
 9922.73 9925.38 9933.36 9943.99 9954.62 9954.86 9965.25 9975.88 9984.33 9986.51
 9988.36 9995.88 9995.88 9996.7010006.8010016.9010018.8510018.8510027.0010037.09
10047.1910050.7310057.2910067.3810077.4810087.5810090.2510097.6510107.7210117.79
10127.8610129.4010137.9210147.9910158.0610168.1310178.2010188.2610198.3310208.40
10215.8310218.4710221.56
  104.33  104.28  103.44  102.94  102.74  102.10  101.52  101.23  100.89  100.24
   99.87   99.80   99.55   99.31   99.04   99.04   99.01   98.94   98.88   98.85
   98.85   98.83   98.83   98.83   98.70   98.61   98.57   98.57   98.39   98.15
   97.85   97.74   97.54   97.28   97.00   96.68   96.61   96.42   96.23   96.02
   95.83   95.80   95.58   95.45   95.33   95.30   95.31   95.32   95.35   95.30
   95.34   95.34   95.34
 -895.67 -895.72 -896.56 -897.06 -897.26 -897.90 -898.48 -898.77 -899.11 -899.76
 -900.13 -900.20 -900.45 -900.69 -900.96 -900.96 -900.99 -901.06 -901.12 -901.15
 -901.15 -901.17   96.33   96.33   96.20   96.11   96.07 -901.43 -901.61 -901.85
 -902.15 -902.26 -902.46 -902.72 -903.00 -903.32 -903.39 -903.58 -903.77 -903.98
 -904.17 -904.20 -904.42 -904.55 -904.67 -904.70 -904.69 -904.68 -904.65 -904.70
 -904.66 -904.66 -904.66
BR Coef=-1 , 0 , 0 ,, 0 ,,,0.8,0,1,0,
WSPro=,,,, 1 ,,,, 0 ,,,, 0 ,,,,-1 ,-1 ,-1 , 0 , 0 , 0 , 0 , 0
BC Design=,, 0 ,, 0 ,,,,,,

Type RM Length L Ch R = 1 ,6423.464,370.210600,370.210600,370.210600
XS GIS Cut Line= 5
871181.471328855784322.964553535871293.541689426784044.596238449
871322.463072866783921.680359095871336.923764557783751.767231703
871275.362311363 783382.62624222
#Sta/Elev= 30
9658.105116.92339709.811116.45249720.591115.25159752.931114.68229763.711113.7147
9774.491111.48179817.611 110.5519828.391 105.9659871.511104.63659893.071 102.794
9908.539102.68299936.191103.67829946.97198.875419968.04497.154949978.31792.98677
 9988.5990.0522610008.2188.5500110019.4191.4876910029.6892.1622210051.8797.49222
10091.1696.5200710114.3896.9787910161.4296.2346110261.8596.1016410292.2694.46429
10322.68 94.730810332.8196.0952610353.0995.9411110495.0298.3886710629.2399.44197
#Mann= 3 , 0 , 0
9658.105  0.0576       09658.105  0.0576       010629.23  0.0576       0
#XS Ineff= 2 , 0
       0                10177.71       0
Bank Sta=9658.105,10629.23
Exp/Cntr=0.3,0.1

Type RM Length L Ch R = 1 ,6053.253,503.571900,503.571900,503.571900
XS GIS Cut Line= 2
871673.134846419784189.203155369871568.294831663783032.347820044
#Sta/Elev= 30
9892.376112.20229926.719111.3597 9936.76107.19089946.801 100.1529966.88393.75415
9976.92493.305829997.00685.6096410017.09 87.634610027.1393.1006310087.3895.79534
10368.5291.49015 10388.688.6120810418.7387.5055310629.59 89.776210649.67 92.2526
10659.7191.7334510669.7588.3540610699.8787.2981610709.9284.8346710800.2887.49818
10840.4591.1560510910.7491.7618210920.7893.3531210940.86100.076810981.02100.0173
10991.06107.3119 11001.1121.816211011.15132.061511031.23 142.63211053.97147.1219
#Mann= 3 , 0 , 0
9892.376  0.0442       09892.376  0.0442       011053.97  0.0442       0
#XS Ineff= 2 , 0
       0                10352.67       0
Bank Sta=9892.376,11053.97
Exp/Cntr=0.3,0.1

Type RM Length L Ch R = 1 ,5549.681,396.122900,396.122900,396.122900
XS GIS Cut Line= 4
872233.486649454783842.146554768872081.649386704783766.227923393
871749.053477794 783726.46102123871593.601042092783025.117474198
#Sta/Elev= 30
9712.70398.092599733.37299.321439766.91396.185959795.765 95.66279811.63492.13651
9833.99591.292339867.53685.2387510151.0188.9015410217.4388.8296910239.4186.29901
10290.6285.5349210434.0289.1808310546.6987.8653910556.9387.3917210567.1883.44074
10608.1585.9882610628.6384.9092910659.3687.2538310690.0987.3900610710.5789.88124
10802.7691.49393   1081394.8554810823.24101.081510853.97101.153210864.21107.6921
10874.46118.4856 10884.7126.942910894.94133.340510925.67145.869210935.79147.5443
#Mann= 3 , 0 , 0
9712.703  0.0588       09712.703  0.0588       010935.79  0.0588       0
#XS Ineff= 2 , 0
       0                   10203       0
Bank Sta=9712.703,10935.79
Exp/Cntr=0.3,0.1

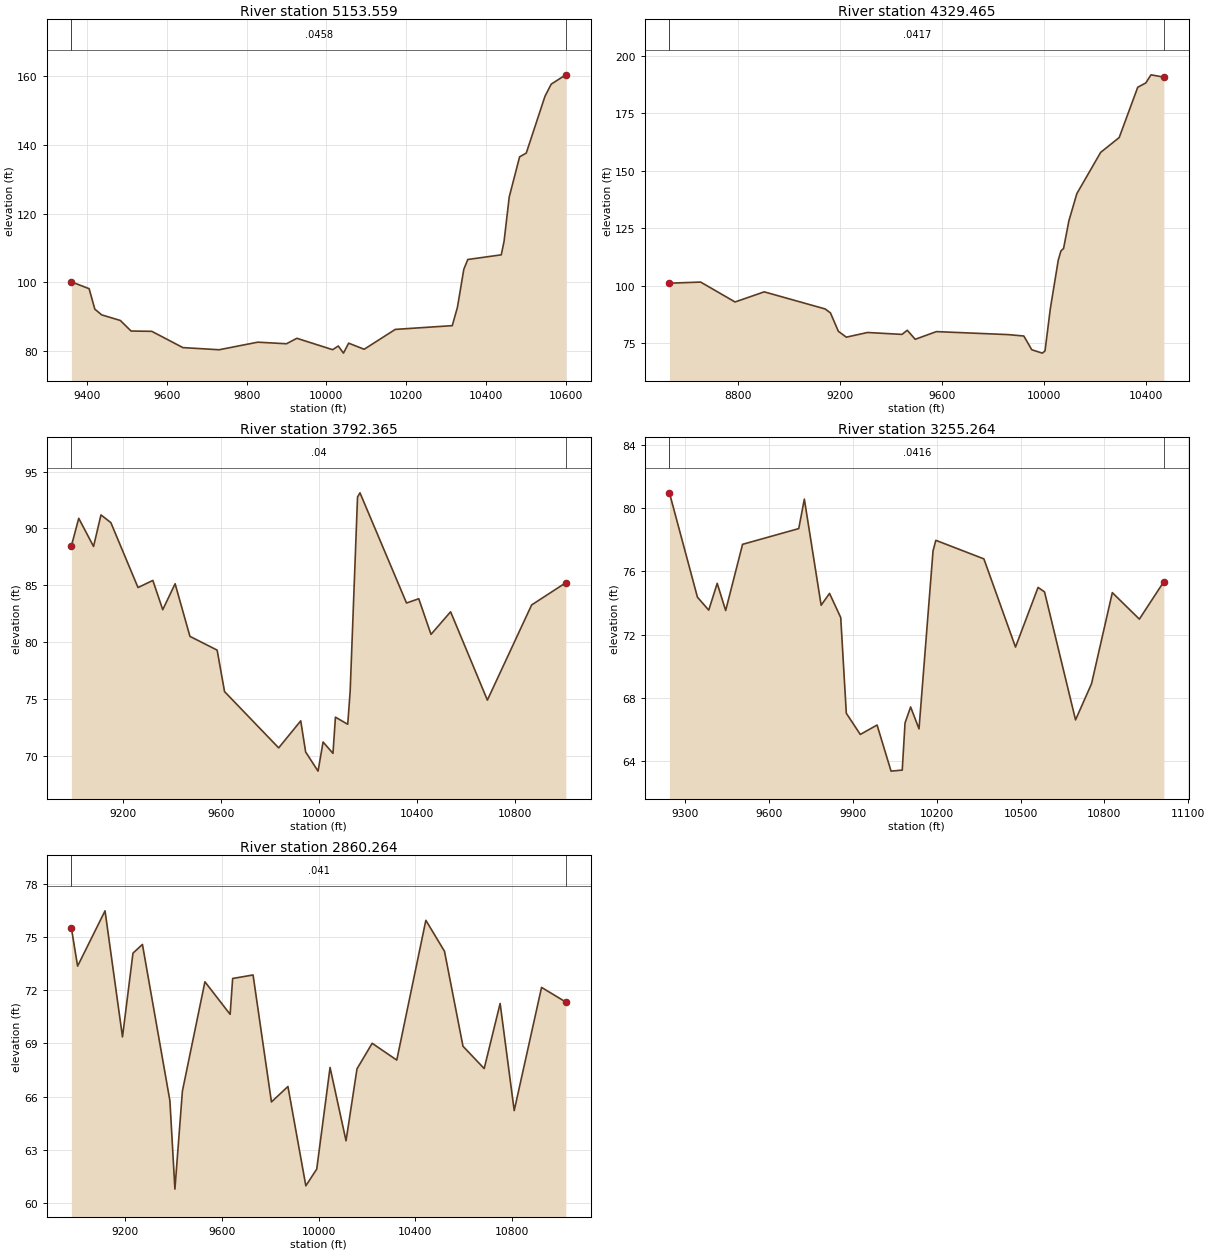
Type RM Length L Ch R = 1 ,5153.559,824.093200,824.093200,824.093200
XS GIS Cut Line= 2
872403.399776846783860.222419396871611.676906705782905.816767722
#Sta/Elev= 30
9360.486100.11319404.96798.135049419.24392.186799436.29390.523919483.28188.88121
9510.19385.809649562.16485.725349640.122 80.99139731.072 80.36049827.85982.56719
9899.97982.106359925.965 83.695110015.8180.3796110029.9181.45616 10042.979.37972
10055.8982.2750810094.8780.5041510172.8386.2839110315.7587.3766810328.74 92.7128
10344.73103.781510354.73106.6282 10438.7107.981710445.68111.908910458.67124.8359
10484.66136.493610501.35137.596210548.34154.1308   10564157.662210600.53160.3626
#Mann= 3 , 0 , 0
9360.486  0.0458       09360.486  0.0458       010600.53  0.0458       0
#XS Ineff= 2 , 0
       0                               0
Bank Sta=9360.486,10600.53
Exp/Cntr=0.3,0.1

Type RM Length L Ch R = 1 ,4329.465,537.100800,537.100800,537.100800
XS GIS Cut Line= 2
872926.850339472784362.809839383872406.017006159 782496.49039495
#Sta/Elev= 30
8531.368101.00588653.679 101.4978788.64792.82743 8902.8597.237849141.63889.79332
9162.40288.075989193.54980.048239224.69577.503469307.75279.543889442.71978.71467
9463.48380.511289494.62976.582189577.68679.923759858.00378.624989920.29578.00576
9951.44272.01272 9992.9770.5559810003.3571.5402910024.1289.9041910055.26111.0438
10065.64 115.03110076.03116.127810096.79 128.10410127.94139.973910221.38157.9631
10294.05164.428110366.73186.320910398.38188.207910418.64191.7313   10469190.7208
#Mann= 3 , 0 , 0
8531.368  0.0417       08531.368  0.0417       0   10469  0.0417       0
#XS Ineff= 2 , 0
       0                               0
Bank Sta=8531.368,10469
Exp/Cntr=0.3,0.1

Type RM Length L Ch R = 1 ,3792.365,537.100900,537.100900,537.100900
XS GIS Cut Line= 6
 873150.63111189784014.799043934873047.402103044783195.080963155
873047.102802293783072.391714159873072.428527119782873.096330661
873076.337828198782573.971991515873036.069745936782006.331608092
#Sta/Elev= 30
8990.59188.456879020.63590.890639081.12788.416499111.37391.191589151.70290.51512
9262.66984.798929323.25385.425569363.64282.850549414.12985.132919474.71280.50345
9585.78379.292329616.03975.640389837.02470.69016 9927.0773.068629947.12770.32817
9997.80268.6436910018.3171.2067310058.7270.2065610068.7573.3937710118.9172.76836
10128.9475.6864810158.9892.7635510168.9993.1346310359.0283.4389910409.02 83.8124
10459.0380.6780710539.0682.6656210689.2474.8948510869.8783.2667211009.4185.22209
#Mann= 3 , 0 , 0
8990.591    0.04       08990.591    0.04       011009.41    0.04       0
#XS Ineff= 2 , 0
       0                               0
Bank Sta=8990.591,11009.41
Exp/Cntr=0.3,0.1

Type RM Length L Ch R = 1 ,3255.264,395.000000,395.000000,395.000000
XS GIS Cut Line= 6
873649.415655255783734.200113922873591.112688214783228.855900437
873591.336724043782841.043585777873575.088962317782681.983392358
873491.934916884782349.522673786873363.472194612782003.798495889
#Sta/Elev= 30
9244.09280.970519344.32574.369239384.74273.549299415.03475.244159445.26573.52558
9505.72877.712859706.69878.70777 9726.7580.573689786.838   73.869816.85774.60844
9856.87973.082199876.87967.026139926.87965.687049986.906 66.282110036.9363.36668
10076.9463.4316910086.94 66.413910106.9467.4247510136.9466.0409410187.0677.29039
10197.09 77.966810369.0476.7924810482.1171.2136810562.8174.9864510585.9674.70575
10696.9166.6086410754.1168.8962310828.4874.6571710925.2172.9817911012.7775.35295
#Mann= 3 , 0 , 0
9244.092  0.0416       09244.092  0.0416       011012.77  0.0416       0
#XS Ineff= 2 , 0
       0                               0
Bank Sta=9244.092,11012.77
Exp/Cntr=0.3,0.1

Type RM Length L Ch R = 1 ,2860.264,0.000000,0.000000,0.000000
XS GIS Cut Line= 6
874306.990309362783879.977414277874090.358840029783103.013577023
874027.630012958782990.821382156873901.919081625782858.634321836
  873829.5509864782751.108392498873488.698337686 782032.06349103
#Sta/Elev= 30
8977.783 75.51079003.53573.367369116.94676.486379189.11769.371989232.45674.09751
9271.59774.590929385.17565.768819405.86260.780819436.89266.313589529.98272.48152
9634.22170.644619644.65872.668349729.05972.86679 9805.0565.700649873.252 66.5725
9947.29960.968649992.32861.9126310047.4367.6467610113.4963.5085810158.8467.56886
10221.6569.0105510323.31 68.063610443.5675.9518210520.6374.2041210597.1268.84466
10684.77 67.5853 10750.771.2596510808.9465.2133810921.98 72.164911022.26 71.3391
#Mann= 3 , 0 , 0
8977.783   0.041       08977.783   0.041       011022.26   0.041       0
#XS Ineff= 2 , 0
       0                               0
Bank Sta=8977.783,11022.26
Exp/Cntr=0.3,0.1